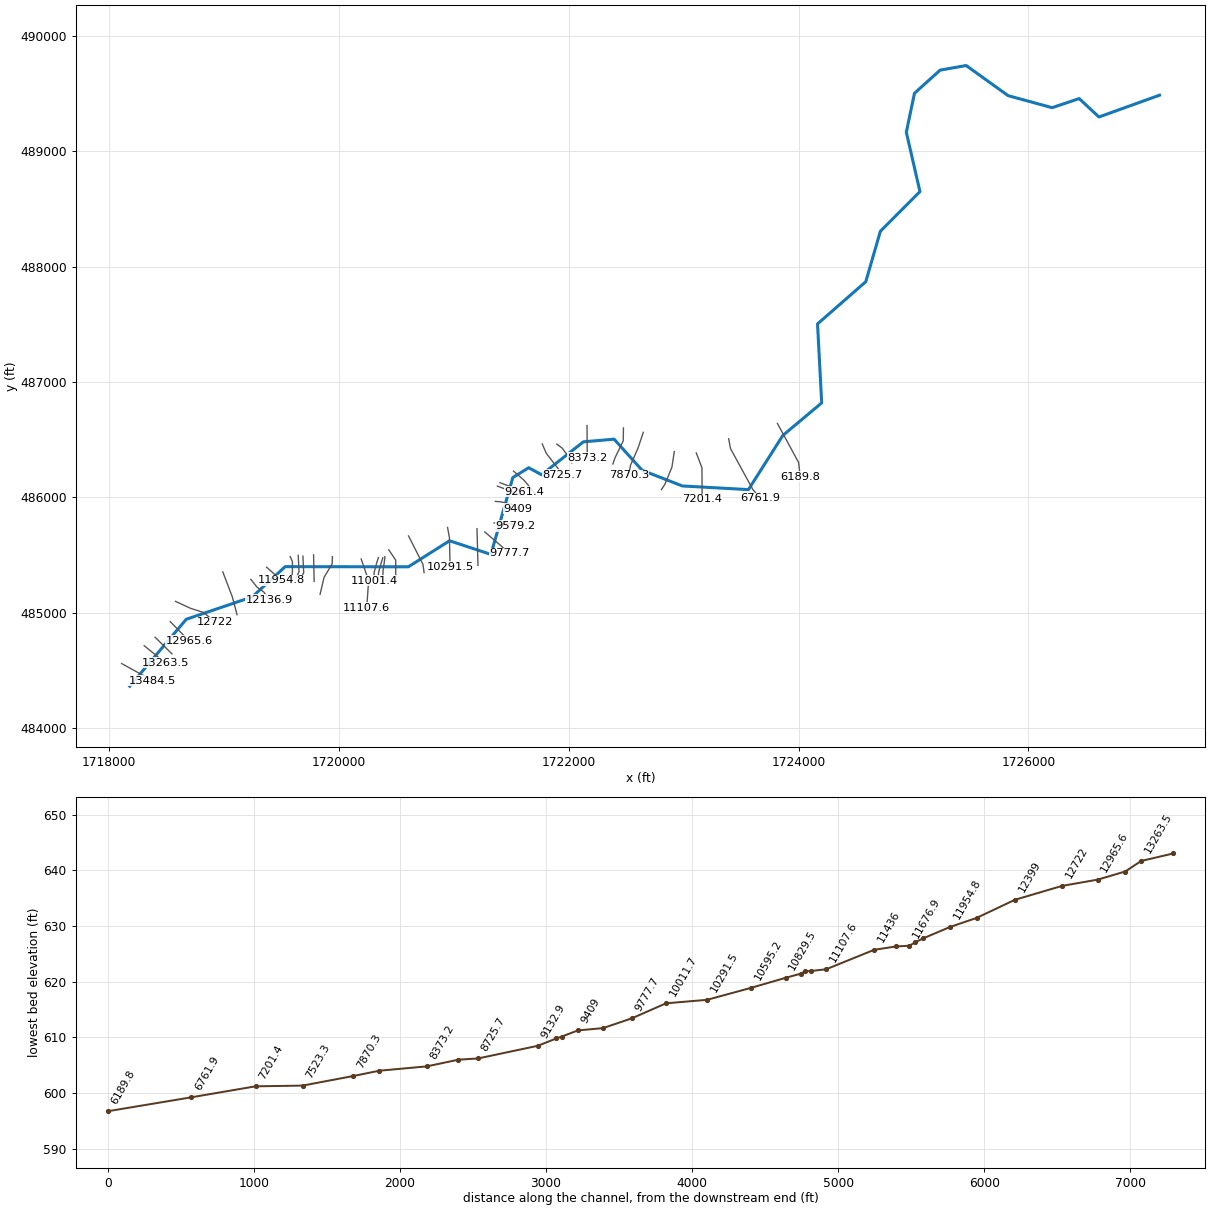
--- FALLSCK.prj (project) ---

Proj Title=FALLSCK
Current Plan=p01
Default Exp/Contr=0,0
English Units
Geom File=g01
Flow File=f01
Plan File=p01
BEGIN DESCRIPTION:
END DESCRIPTION:
DSS Export Rating Curves= 0
DSS Export Rating Curve Sorted= 0
DSS Export Volume Flow Curves= 0
DXF OffsetX= 0
DXF OffsetY= 0
DXF ScaleX= 0
DXF ScaleY= 0

--- FALLSCK.p01 (plan) ---

Plan Title=Floodplain
Program Version=4.00
Geom File=g01
Flow File=f01
K Sum by GR=0
Std Step Tol=0.01
Critical Tol=0.01
Num of Std Step Trials=20
Max Error Tol=0.3
Flow Tol Ratio=0.001
Split Flow NTrial=30
Split Flow Tol=0.02
Split Flow Ratio=0.02
Log Output Level=0
Friction Slope Method=1
Unsteady Friction Slope Method=2
Unsteady Bridges Friction Slope Method=1
Global Log Level=0
CheckData=False
Run HTab=0
Run UNet=0
Run PostProcess=0
UNET Theta=0
UNET Theta Warmup=0
UNET ZTol=0
UNET ZSATol=0
UNET MxIter=0
UNET MaxInSteps=0
UNET DtIC=0
UNET DtMin=0
UNET MaxCRTS=0
UNET WFStab=0
UNET SFStab=0
UNET WFX=0
UNET SFX=0
UNET DSS MLevel=0
UNET DZMax Abort=0
UNET Convert EG Bridges=0
UNET Use Existing IB Tables=0
UNET Froude Limit=0
UNET Froude Power=0
Write IC File=0
Echo Input=False
Echo Output=False
Write Detailed=0

--- FALLSCK.f01 (steady flow) ---

Flow Title=NFF Regression Equation
Program Version=4.10
Number of Profiles= 1
Profile Names=P100yr
River Rch & RM=FALLSCK,Main            ,13484.5
 967.814
River Rch & RM=FALLSCK,Main            ,12136.9
1010.992
River Rch & RM=FALLSCK,Main            ,11107.6
1089.329
River Rch & RM=FALLSCK,Main            ,8725.7
 1158.63
River Rch & RM=FALLSCK,Main            ,3136
1272.497
River Rch & RM=FALLSCK,Main            ,431.9
1402.235
Boundary for River Rch & Prof#=FALLSCK,Main            , 1
Up Type= 0
Dn Type= 3
Dn Slope=0.002
DSS Import GetInterval= 0
DSS Import GetPeak= 0
DSS Import FillOption= 0

--- FALLSCK.g01 (geometry) ---

Geom Title=USGS 10m DEM
Program Version=4.10

River Reach=FALLSCK         ,Main
Reach XY= 30
     1718180.142      484362.521     1718671.462      484942.382
     1719246.114      485136.826      1719532.66      485398.656
     1720604.414      485397.403     1720962.921      485623.097
     1721322.296      485505.042     1721513.476      486171.549
     1721651.617       486256.32     1721763.384      486195.431
     1722126.983      486480.736     1722394.332      486503.941
     1722638.268      486234.208     1722988.262      486098.216
     1723563.615      486066.673      1723862.73      486536.324
     1724200.768       486818.41     1724164.517      487503.146
     1724584.448      487868.757     1724711.184      488306.257
     1725055.802      488650.007     1724937.086      489164.604
     1725008.059      489502.437      1725231.15      489702.958
     1725457.738      489742.949     1725823.164      489481.604
     1726205.976      489377.437     1726441.219       489456.43
     1726613.094      489296.708     1727140.371      489485.863

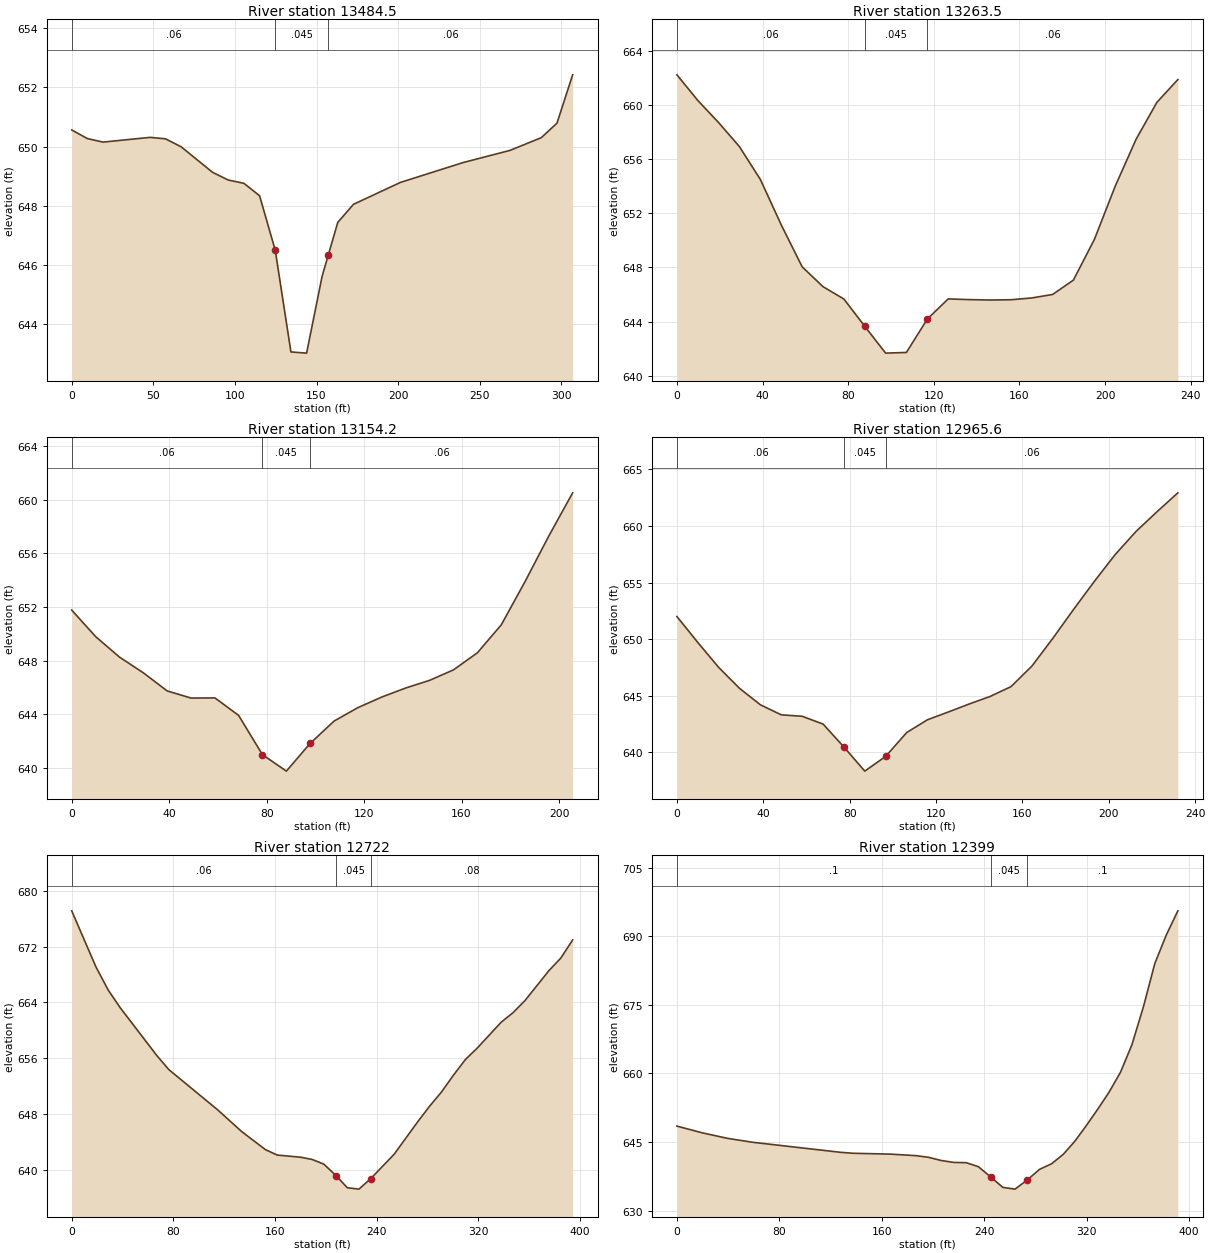
Type RM Length L Ch R = 1 ,13484.5 ,225.1,221.1,217.1
XS GIS Cut Line= 2
     1718109.832      484558.611     1718378.929      484411.042
#Sta/Elev= 23
       0  650.56     9.6  650.27    19.2  650.15      48  650.31    57.5  650.26
    67.1  649.99    86.3  649.13    95.9  648.87   105.5  648.76   115.1  648.34
   124.7   646.5   134.3  643.07   143.9  643.03   153.4  645.62  157.16 646.333
     163  647.44   172.6  648.05   201.4  648.79   239.8  649.46   268.5  649.87
   287.7   650.3   297.3  650.79   306.9  652.42
#Mann= 3 , 0 , 0
       0     .06       0   124.7    .045       0  157.16     .06       0
Bank Sta=124.7,157.16
XS Rating Curve= 0 ,0
Exp/Cntr=0.3,0.1

Type RM Length L Ch R = 1 ,13263.5 ,111.5,109.3,107
XS GIS Cut Line= 2
     1718306.012      484713.125     1718488.304      484566.424
#Sta/Elev= 27
       0  662.21     9.8  660.31    19.5  658.68    29.2  656.91      39  654.48
    48.8  651.11    58.5  648.04    68.2  646.58      78  645.66    87.8  643.64
    92.9   642.6    97.5  641.67   107.2  641.72   107.9   641.9     117  644.19
   126.7  645.67   136.5  645.62   146.2  645.59     156  645.61   165.7  645.74
   175.5     646   185.2  647.06     195  650.06   204.7  653.98   214.5  657.46
   224.2  660.18     234  661.86
#Mann= 3 , 0 , 0
       0     .06       0    87.8    .045       0     117     .06       0
Bank Sta=87.8,117
XS Rating Curve= 0 ,0
Exp/Cntr=0.3,0.1

Type RM Length L Ch R = 1 ,13154.2 ,189,188.5,188.1
XS GIS Cut Line= 2
      1718400.63       484786.91     1718547.332      484642.813
#Sta/Elev= 24
       0  651.77     9.8   649.8    19.6  648.27    29.4   647.1    39.2  645.75
      49  645.22    58.8  645.23    68.5  643.93    78.3     641    80.9  640.68
    88.1  639.78    95.9  641.43    97.9  641.85   107.7  643.51   117.5  644.51
   127.3   645.3   137.1  645.97   146.9  646.54   156.7  647.32   166.5  648.59
   176.3  650.67     186  653.87   195.8  657.28   205.6   660.5
#Mann= 3 , 0 , 0
       0     .06       0    78.3    .045       0    97.9     .06       0
Bank Sta=78.3,97.9
XS Rating Curve= 0 ,0
Exp/Cntr=0.3,0.1

Type RM Length L Ch R = 1 ,12965.6 ,227,243.7,260.3
XS GIS Cut Line= 2
     1718532.575      484922.327     1718694.901      484756.528
#Sta/Elev= 27
       0  651.99     9.7  649.69    19.3   647.5      29  645.64    38.7  644.18
    48.3   643.3      58  643.17    67.7  642.48    77.3  640.46    81.2   639.6
      87  638.32    96.2  639.56    96.7  639.63   106.4  641.73     116  642.86
   125.7  643.55   135.4  644.26     145  644.92   154.7  645.79   164.4  647.61
     174  650.04   183.7  652.62   193.4  655.12     203  657.48   212.7  659.53
   222.4  661.27     232  662.93
#Mann= 3 , 0 , 0
       0     .06       0    77.3    .045       0    96.7     .06       0
Bank Sta=77.3,96.7
XS Rating Curve= 0 ,0
Exp/Cntr=0.3,0.1

Type RM Length L Ch R = 1 ,12722   ,350.6,323,295
XS GIS Cut Line= 4
     1718578.582      485097.674      1718708.79      485037.778
     1718822.505       485001.32     1718924.068      484917.986
#Sta/Elev= 30
       0  677.15    19.1  669.09    28.7  665.78    38.2  663.23    66.9  656.39
    76.4  654.36   114.7   648.6   133.8  645.45   152.5  642.86   161.7  642.09
   180.1  641.78   189.2  641.46   198.4  640.78   208.3  639.08   216.8   637.4
     226   637.2   235.2   638.7   253.6  642.19   272.1  646.84   281.5  649.09
   290.9  651.14   300.3  653.55   309.7   655.8     319  657.44   337.8  661.15
   347.2  662.53   356.6  664.27   375.4  668.56   384.7  670.35   394.1  672.97
#Mann= 3 , 0 , 0
       0     .06       0   208.3    .045       0   235.2     .08       0
Bank Sta=208.3,235.2
XS Rating Curve= 0 ,0
Exp/Cntr=0.3,0.1

Type RM Length L Ch R = 1 ,12399   ,246.7,262.1,277.2
XS GIS Cut Line= 4
      1718990.04      485352.882     1719070.769      485141.945
     1719088.998      485077.709     1719113.304      484982.223
#Sta/Elev= 30
       0  648.48    19.6  647.02    39.3  645.81    58.9  644.95   127.7  642.75
   137.5  642.54   166.9  642.35   186.6  642.02   196.4  641.66   206.2  640.97
     216  640.54   225.9  640.48   235.4  639.61   244.9  637.39   254.5  635.08
     264   634.7   273.6   636.7   283.1  639.01   292.6  640.25   301.6  642.28
   310.6  645.12   319.5  648.51   328.5  652.12   337.4  655.86   346.4  660.26
   355.3  666.25   364.3  674.57   373.2  684.04   382.2  690.28   391.2  695.54
#Mann= 3 , 0 , 0
       0      .1       0   244.9    .045       0   273.6      .1       0
Bank Sta=244.9,273.6
XS Rating Curve= 0 ,0
Exp/Cntr=0.3,0.1

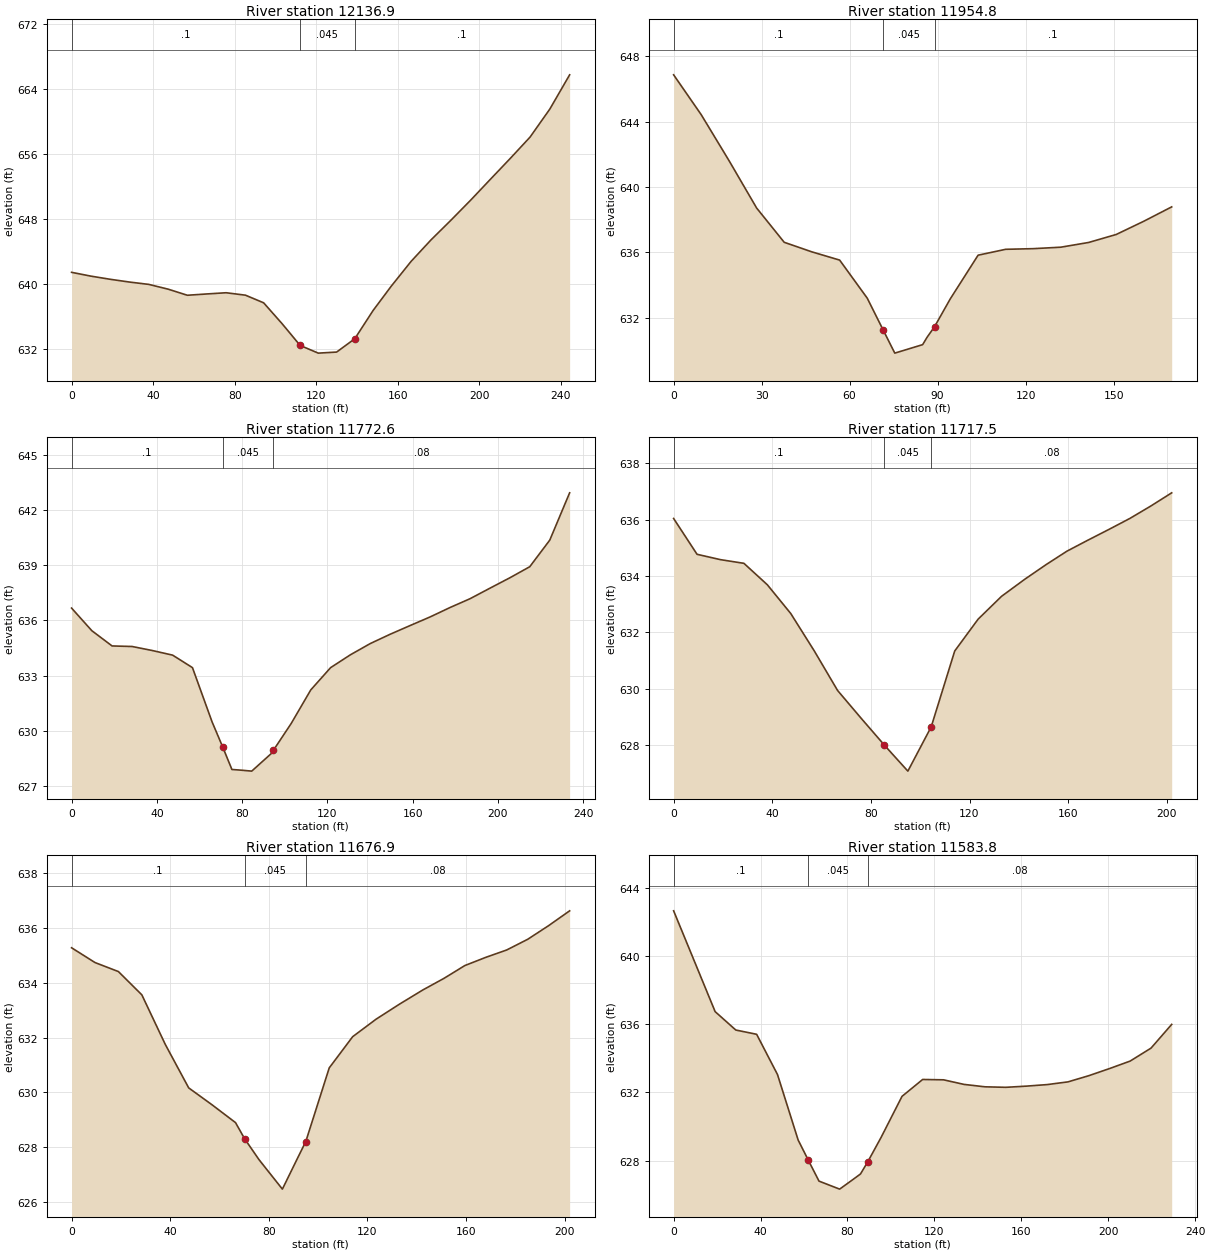
Type RM Length L Ch R = 1 ,12136.9 ,184.3,182.1,179.9
XS GIS Cut Line= 4
     1719233.964      485288.646     1719286.915      485221.806
     1719345.075      485180.139     1719397.158      485109.827
#Sta/Elev= 29
       0  641.42     9.5  640.95      19  640.56    28.4  640.22    37.9  639.93
    47.4  639.34    56.8  638.59    66.3  638.75    75.8   638.9    85.3   638.6
    94.2  637.66   103.2   635.1   107.4  633.83   112.1   632.4     121  631.45
   122.4  631.47     130  631.58   138.9  633.22   147.9  636.71   156.8  639.71
   166.5  642.76   176.3  645.42     186  647.83   195.7  650.31   205.4  652.89
   215.2  655.48   224.9  658.11   234.6  661.57   244.3  665.79
#Mann= 3 , 0 , 0
       0      .1       0   112.1    .045       0   138.9      .1       0
Bank Sta=112.1,138.9
XS Rating Curve= 0 ,0
Exp/Cntr=0.3,0.1

Type RM Length L Ch R = 1 ,11954.8 ,201.5,182.1,162.7
XS GIS Cut Line= 2
     1719370.769      485394.028     1719498.373      485282.049
#Sta/Elev= 22
       0  646.87     9.4  644.43    18.9  641.61    28.3  638.71    37.7  636.61
    47.2  636.02    56.6  635.52      66  633.19    71.4  631.25    75.4  629.82
    84.9  630.34    86.4  630.79   88.96  631.44    94.3  633.14   103.8  635.82
   113.2  636.18   122.6  636.22     132  636.31   141.5   636.6   150.9  637.09
   160.3   637.9   169.8  638.78
#Mann= 3 , 0 , 0
       0      .1       0    71.4    .045       0   88.96      .1       0
Bank Sta=71.4,88.96
XS Rating Curve= 0 ,0
Exp/Cntr=0.3,0.1

Type RM Length L Ch R = 1 ,11772.6 ,54.1,55.2,56.3
XS GIS Cut Line= 4
     1719576.498      485486.042     1719595.596      485442.639
     1719595.596      485359.306     1719586.047      485256.875
#Sta/Elev= 29
       0  636.67     9.5  635.44      19  634.61    28.4  634.58    37.9  634.36
    47.4  634.11    56.7  633.43    65.9  630.48   70.86  629.12    75.2  627.89
    79.7  627.85    84.5   627.8    93.7  628.76    94.7  628.94     103  630.39
   112.2  632.22   121.5  633.43   130.8  634.13   140.1  634.74   149.5  635.25
   158.8  635.72   168.2  636.19   177.5   636.7   186.9  637.18   196.2  637.75
   205.6  638.32   214.9  638.92   224.3  640.37   233.6  642.94
#Mann= 3 , 0 , 0
       0      .1       0   70.86    .045       0    94.7     .08       0
Bank Sta=70.86,94.7
XS Rating Curve= 0 ,0
Exp/Cntr=0.3,0.1

Type RM Length L Ch R = 1 ,11717.5 ,40.6,40.6,40.6
XS GIS Cut Line= 3
     1719645.943      485497.327     1719652.887      485354.966
     1719627.714      485301.146
#Sta/Elev= 25
       0  636.04     9.5  634.77      19  634.58    28.5  634.45      38  633.69
    47.5  632.67      57  631.35    66.5  629.94      76  628.96    85.5     628
    89.1  627.65      95  627.08   104.1  628.59   104.5  628.66     114  631.34
   123.5  632.47     133  633.28   142.5  633.89     151   634.4   159.5  634.88
     168  635.27   176.5  635.65     185  636.04   193.5  636.48     202  636.95
#Mann= 3 , 0 , 0
       0      .1       0    85.5    .045       0   104.5     .08       0
Bank Sta=85.5,104.5
XS Rating Curve= 0 ,0
Exp/Cntr=0.3,0.1

Type RM Length L Ch R = 1 ,11676.9 ,93.6,93.1,92.5
XS GIS Cut Line= 3
     1719686.741      485489.514     1719693.686      485347.153
     1719668.512      485293.334
#Sta/Elev= 26
       0  635.28     9.5  634.74      19  634.41    28.5  633.56      38  631.75
    47.5  630.16      57  629.54    66.5  628.89   70.19   628.3      76  627.54
    76.7  627.46    85.5  626.46    91.7   627.6      95   628.2   104.5  630.89
     114  632.03   123.5  632.67     133  633.22   142.5  633.74     151  634.16
   159.5  634.63     168  634.93   176.5   635.2     185  635.59   193.5  636.09
     202  636.63
#Mann= 3 , 0 , 0
       0      .1       0   70.19    .045       0      95     .08       0
Bank Sta=70.19,95
XS Rating Curve= 0 ,0
Exp/Cntr=0.3,0.1

Type RM Length L Ch R = 1 ,11583.8 ,160.8,147.8,135.1
XS GIS Cut Line= 2
     1719779.623      485499.931     1719784.832      485270.764
#Sta/Elev= 29
       0  642.65     9.6  639.68    19.1  636.74    28.6  635.66    38.2  635.41
    47.8  633.05    57.3  629.21      62  628.02    66.9   626.8    67.7  626.76
    76.4  626.33    82.7  626.91      86  627.22   89.24  627.91    95.5  629.37
   105.1  631.77   114.6  632.76   124.2  632.74   133.7  632.47   143.3  632.33
   152.8   632.3   162.4  632.37   171.9  632.46   181.5  632.62     191  632.98
   200.6   633.4   210.1  633.84   219.7   634.6   229.2  635.99
#Mann= 3 , 0 , 0
       0      .1       0      62    .045       0   89.24     .08       0
Bank Sta=62,89.24
XS Rating Curve= 0 ,0
Exp/Cntr=0.3,0.1

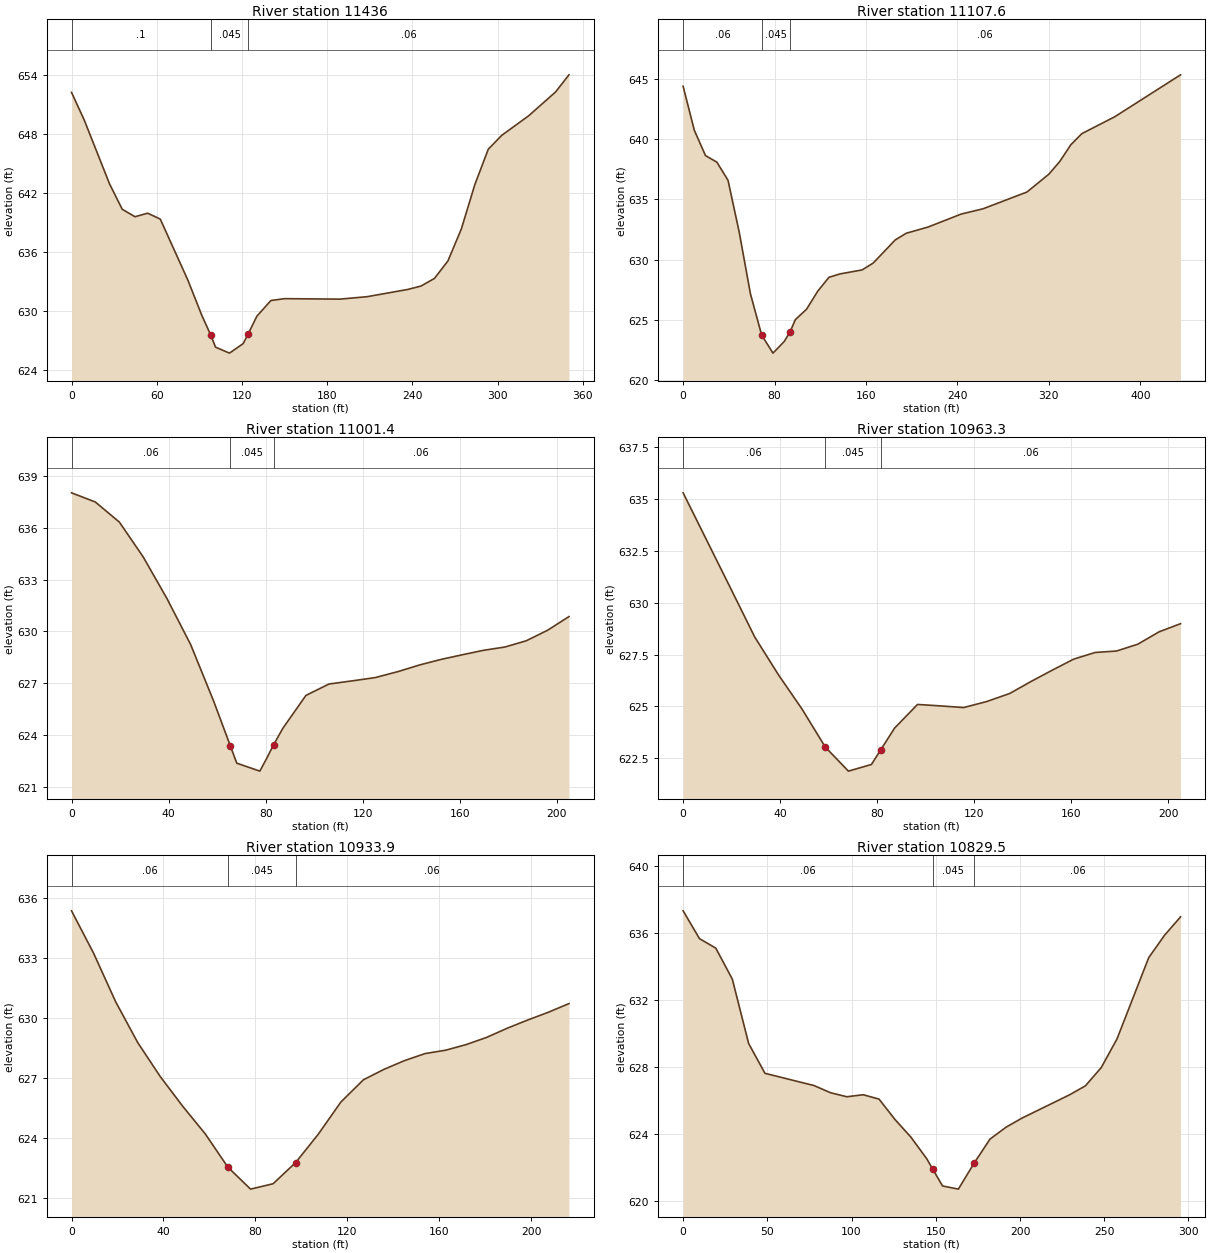
Type RM Length L Ch R = 1 ,11436   ,308.3,328.4,348
XS GIS Cut Line= 4
     1719943.252      485485.608     1719941.516      485423.108
     1719870.986      485306.571     1719836.264      485159.002
#Sta/Elev= 30
       0  652.24     8.9  649.45    26.8  642.93    35.7  640.36    44.7   639.6
    53.6  639.96    62.5  639.36      82  633.13    91.7  629.59   98.14  627.53
   101.4  626.34   111.2  625.73   120.9   626.7  124.36  627.68   130.6   629.5
   140.4  631.08   150.1  631.27     189  631.22   208.2  631.47   236.6   632.2
   246.1  632.55   255.6  633.33   265.1  635.11   274.5  638.35     284  642.86
   293.5  646.47     303  647.88   321.9  649.86   340.9  652.29   350.3  654.03
#Mann= 3 , 0 , 0
       0      .1       0   98.14    .045       0  124.36     .06       0
Bank Sta=98.14,124.36
XS Rating Curve= 0 ,0
Exp/Cntr=0.3,0.1

Type RM Length L Ch R = 1 ,11107.6 ,119.7,106.2,92.5
XS GIS Cut Line= 4
     1720193.686      485465.209     1720235.353      485344.549
      1720258.79      485281.181      1720242.08      485041.815
#Sta/Elev= 30
       0  644.37     9.8  640.72    19.6  638.62    29.5  638.08    39.3  636.57
    49.1  632.26    58.9  627.16    68.7  623.74    78.6  622.24    88.4   623.2
   93.45  623.98    98.2  625.02     108  625.88   117.8  627.38   127.6  628.53
   137.3  628.81   156.6  629.14   166.3  629.71   185.6  631.63   195.2  632.18
   214.4   632.7   243.2  633.77   262.4  634.21   300.8   635.6     320  637.08
   329.6  638.14   339.2  639.52   348.8  640.44   377.6  641.84   435.2  645.32
#Mann= 3 , 0 , 0
       0     .06       0    68.7    .045       0   93.45     .06       0
Bank Sta=68.7,93.45
XS Rating Curve= 0 ,0
Exp/Cntr=0.3,0.1

Type RM Length L Ch R = 1 ,11001.4 ,38.1,38.1,38.2
XS GIS Cut Line= 4
     1720343.859      485478.229     1720329.103      485431.354
     1720306.533      485348.889     1720303.929      485278.577
#Sta/Elev= 26
       0  638.02     9.8  637.49    19.7  636.33    29.5  634.32    39.3  631.91
    49.1  629.24    58.6  625.96    65.4   623.4    68.1  622.38    77.6  621.92
    80.4  622.65   83.26  623.44    87.1   624.4    96.6   626.3   106.1  626.96
   115.6  627.14   125.1  627.33   134.6  627.68   143.4  628.06   152.2  628.38
     161  628.65   169.8  628.91   178.6   629.1   187.4  629.46   196.2  630.07
     205  630.86
#Mann= 3 , 0 , 0
       0     .06       0    65.4    .045       0   83.26     .06       0
Bank Sta=65.4,83.26
XS Rating Curve= 0 ,0
Exp/Cntr=0.3,0.1

Type RM Length L Ch R = 1 ,10963.3 ,26.6,29.4,32.2
XS GIS Cut Line= 4
     1720382.054      485475.625     1720367.297       485428.75
     1720344.728      485346.285     1720342.123      485275.973
#Sta/Elev= 25
       0  635.31     9.8     633    19.7  630.67    29.5  628.35    39.3  626.52
    49.1  624.85    58.6  623.03    66.4  622.08    68.1  621.87    77.6  622.19
    81.4  622.89    87.1  623.94    96.6  625.09   106.1  625.02   115.6  624.94
   125.1  625.23   134.6  625.62   143.4   626.2   152.2  626.75     161  627.28
   169.8   627.6   178.6  627.67   187.4     628   196.2   628.6     205  628.99
#Mann= 3 , 0 , 0
       0     .06       0    58.6    .045       0    81.4     .06       0
Bank Sta=58.6,81.4
XS Rating Curve= 0 ,0
Exp/Cntr=0.3,0.1

Type RM Length L Ch R = 1 ,10933.9 ,101.1,104.5,107.9
XS GIS Cut Line= 4
     1720400.283      485486.042     1720397.679      485457.396
      1720383.79      485360.174     1720381.186      485270.764
#Sta/Elev= 26
       0  635.37     9.6  633.25    19.2  630.82    28.8  628.78    38.6  627.08
    48.4  625.59    58.2  624.21      68  622.55    75.1  621.76    77.9  621.45
    87.7  621.72    90.1  621.98    97.5  622.78   107.3  624.19   117.2  625.81
     127  626.92   135.9  627.44   144.9  627.88   153.8  628.23   162.8   628.4
   171.7  628.68   180.6  629.04   189.6   629.5   198.5  629.91   207.5   630.3
   216.4  630.73
#Mann= 3 , 0 , 0
       0     .06       0      68    .045       0    97.5     .06       0
Bank Sta=68,97.5
XS Rating Curve= 0 ,0
Exp/Cntr=0.3,0.1

Type RM Length L Ch R = 1 ,10829.5 ,223.6,234.2,244.8
XS GIS Cut Line= 3
     1720434.137      485544.202     1720494.033       485455.66
     1720494.901      485267.292
#Sta/Elev= 28
       0  637.33     9.7  635.67    19.4   635.1    29.2  633.25    38.9   629.4
    48.6  627.62    77.7  626.89    87.5  626.46    97.2  626.22   106.9  626.34
   116.3  626.08   125.7  624.87   135.2  623.81   144.6  622.52   148.1  621.91
     154  620.89   163.4   620.7   172.8  622.26   182.2  623.69   191.7   624.4
   201.1  624.94   229.3  626.33   238.8  626.87   248.2  627.96   257.6  629.68
   276.4  634.53   285.8  635.87   295.3  636.97
#Mann= 3 , 0 , 0
       0     .06       0   148.1    .045       0   172.8     .06       0
Bank Sta=148.1,172.8
XS Rating Curve= 0 ,0
Exp/Cntr=0.3,0.1

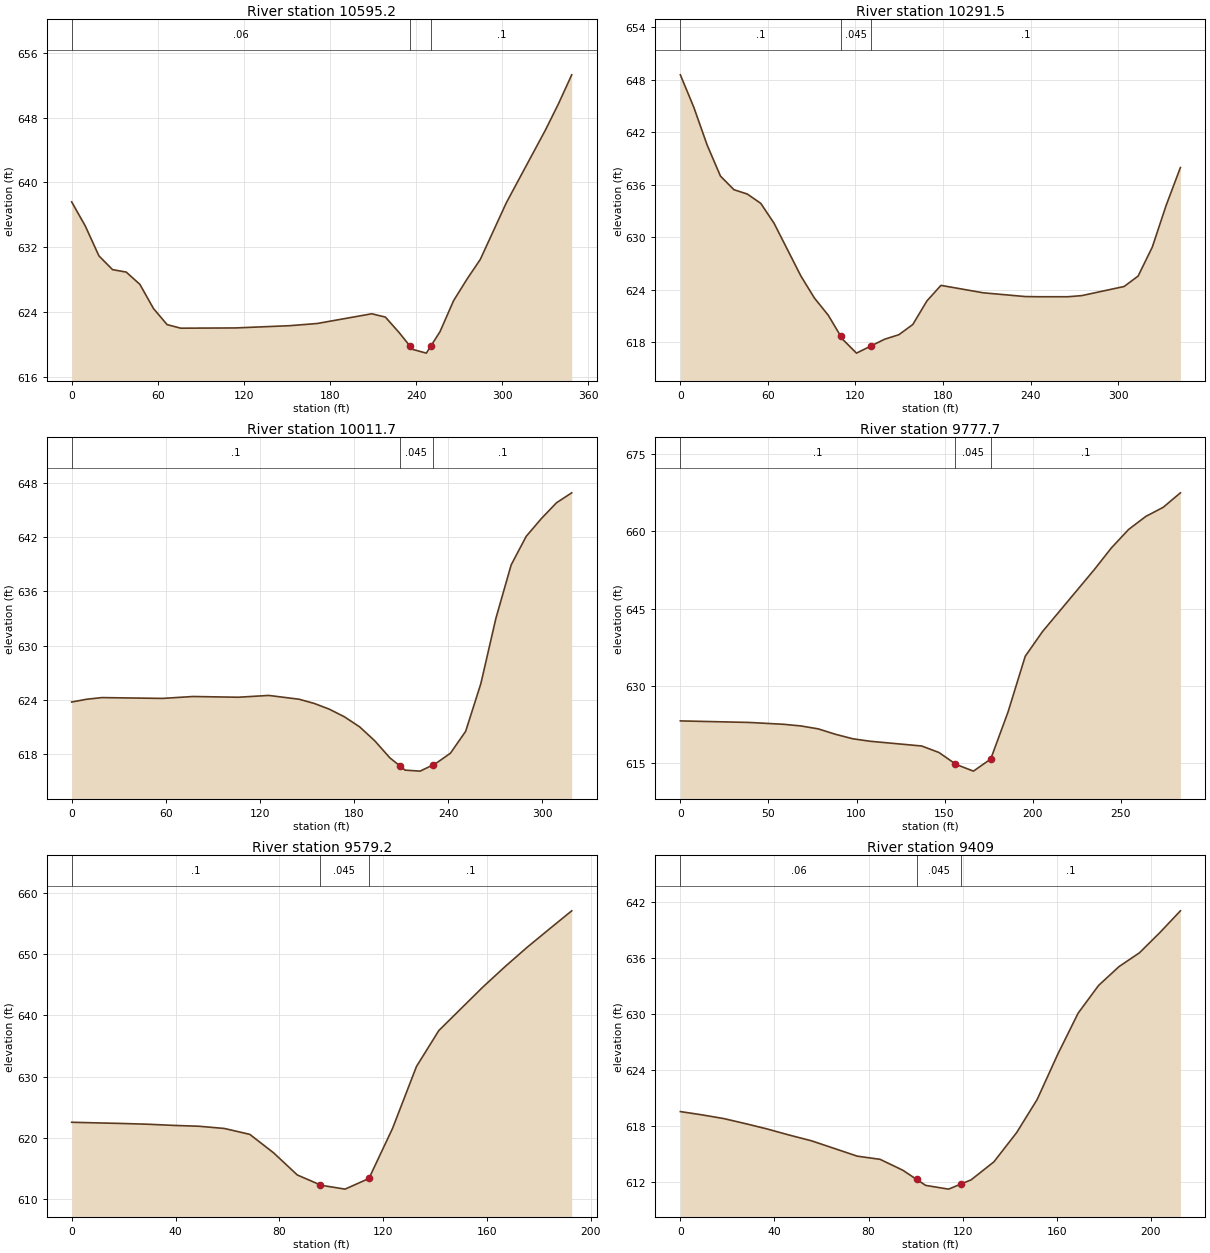
Type RM Length L Ch R = 1 ,10595.2 ,314.9,303.8,290.7
XS GIS Cut Line= 3
     1720606.012      485664.861     1720731.012      485419.202
     1720741.429      485347.153
#Sta/Elev= 27
       0   637.6     9.5  634.62      19  630.93    28.5  629.23      38  628.93
    47.5  627.42      57  624.43    66.5  622.44      76     622   114.1  622.03
   152.1  622.31   171.1  622.58   209.1  623.78   218.6  623.37   228.1  621.47
   235.5  619.84   237.6  619.38   247.1  618.92   250.5  619.86   256.6  621.56
   266.1   625.4   275.6   628.1   284.7  630.49   302.9  637.51   330.2  646.51
   339.3  649.76   348.4  653.29
#Mann= 3 , 0 , 0
       0     .06       0   235.5    .045       0   250.5      .1       0
Bank Sta=235.5,250.5
XS Rating Curve= 0 ,0
Exp/Cntr=0.3,0.1

Type RM Length L Ch R = 1 ,10291.5 ,278.7,279.8,282
XS GIS Cut Line= 3
     1720945.422      485738.646     1720961.915      485648.368
     1720967.123        485397.5
#Sta/Elev= 30
       0  648.54     9.2  644.84    18.4   640.5    27.5  636.97    36.7  635.42
    45.9  634.92    55.1  633.86    64.2  631.59    82.6  625.56    91.8  623.06
   101.4  621.07     110  618.66   111.1  618.35   120.7  616.75   130.4  617.55
     140  618.34   149.7  618.85   159.3  620.02     169  622.72   178.6  624.49
   207.6  623.64   236.5  623.21   246.2  623.19   265.5  623.19   275.1  623.32
   304.1  624.36   313.7  625.55   323.4  628.85     333  633.66   342.7  637.95
#Mann= 3 , 0 , 0
       0      .1       0     110    .045       0   130.4      .1       0
Bank Sta=110,130.4
XS Rating Curve= 0 ,0
Exp/Cntr=0.3,0.1

Type RM Length L Ch R = 1 ,10011.7 ,215.5,234,253.3
XS GIS Cut Line= 2
     1721201.498      485728.229     1721210.179      485409.653
#Sta/Elev= 28
       0  623.77     9.7  624.08    19.3  624.26    57.9  624.17    77.3  624.38
   106.2   624.3   125.6   624.5   144.9  624.08   154.5  623.62   164.2  622.98
   173.8  622.14   183.5  621.03   193.2  619.48   202.8   617.6  209.26   616.7
   212.5  616.24   222.1  616.13   230.2  616.81   231.8  616.94   241.4  618.11
   251.1  620.53   260.8  625.81   270.4  633.04   280.1  638.93   289.7  642.09
   299.4  644.06     309   645.8   318.7   646.9
#Mann= 3 , 0 , 0
       0      .1       0  209.26    .045       0   230.2      .1       0
Bank Sta=209.26,230.2
XS Rating Curve= 0 ,0
Exp/Cntr=0.3,0.1

Type RM Length L Ch R = 1 ,9777.7  ,182.8,198.5,214.1
XS GIS Cut Line= 2
     1721269.207      485699.584     1721485.353      485515.556
#Sta/Elev= 23
       0  623.19    39.2  622.89    58.7  622.53    68.5  622.21    78.3  621.64
    88.1  620.59    97.9  619.72   107.7  619.24     137  618.32   146.8  617.06
   156.1  614.85   156.6  614.73   166.4  613.44   176.2  615.79     186  624.89
   195.8  635.74   205.6  640.53   234.9  652.52   244.7  656.77   254.5  660.36
   264.3   662.9   274.1  664.65   283.9  667.47
#Mann= 3 , 0 , 0
       0      .1       0   156.1    .045       0   176.2      .1       0
Bank Sta=156.1,176.2
XS Rating Curve= 0 ,0
Exp/Cntr=0.3,0.1

Type RM Length L Ch R = 1 ,9579.2  ,174.8,170.2,165.6
XS GIS Cut Line= 4
     1721349.936      485777.709     1721418.512      485778.577
     1721482.748      485777.709     1721536.568      485751.667
#Sta/Elev= 24
       0  622.57     9.8  622.47    19.6  622.37    29.4  622.25    39.2  622.06
      49  621.92    58.8  621.56    68.6   620.6    77.8  617.58    86.9  613.98
    95.5  612.41    96.1   612.3   105.3  611.67   110.5  612.65   114.5  613.41
   123.6  621.58   132.8  631.66   141.4  637.51   149.9  641.07   158.4  644.62
     167  647.97   175.5  651.12   184.1  654.11   192.6  657.04
#Mann= 3 , 0 , 0
       0      .1       0    95.5    .045       0   114.5      .1       0
Bank Sta=95.5,114.5
XS Rating Curve= 0 ,0
Exp/Cntr=0.3,0.1

Type RM Length L Ch R = 1 ,9409    ,115,111.7,108.4
XS GIS Cut Line= 4
     1721361.221      485964.341     1721407.228      485960.868
     1721501.846      485940.035     1721560.005      485901.841
#Sta/Elev= 27
       0  619.57     9.2  619.22    18.5  618.82    27.7  618.28    36.9  617.71
    46.1  617.07    55.8  616.44    65.5  615.62    75.2   614.8    84.9  614.46
    94.6  613.29   100.4  612.32   104.3  611.67     114  611.27   115.4  611.41
  119.35  611.83   123.6  612.26   133.3  614.19     143  617.33   151.7  620.87
   160.4  625.68   169.1   630.1   177.8  633.07   186.5  635.09   195.2  636.57
   203.9  638.74   212.6  641.06
#Mann= 3 , 0 , 0
       0     .06       0   100.4    .045       0  119.35      .1       0
Bank Sta=100.4,119.35
XS Rating Curve= 0 ,0
Exp/Cntr=0.3,0.1

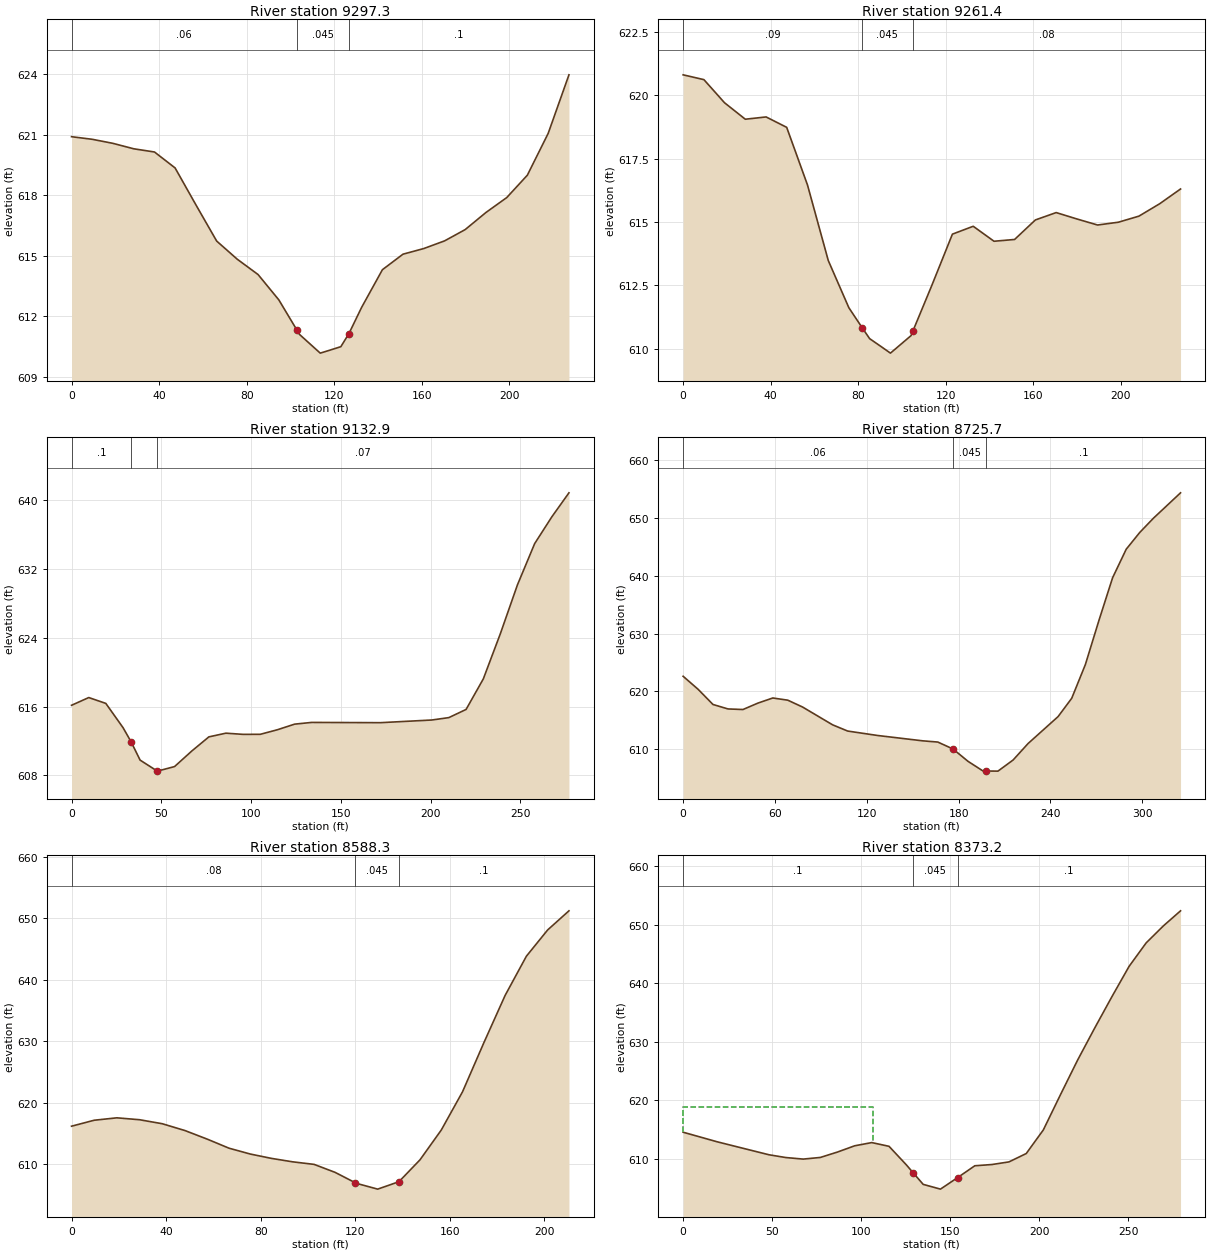
Type RM Length L Ch R = 1 ,9297.3  ,35.9,36,36
XS GIS Cut Line= 2
     1721378.582      486097.153     1721591.255      486017.292
#Sta/Elev= 28
       0   620.9     9.5  620.77    18.9  620.57    28.4   620.3    37.9  620.14
    47.3  619.35    56.8  617.52    66.3  615.72    75.7  614.82    85.2  614.06
    94.7   612.8   102.8  611.33   104.1  611.09   113.6  610.16   117.8   610.3
     123  610.48  126.66  611.12   132.5  612.43     142   614.3   151.4  615.07
   160.9  615.35   170.4  615.73   179.8  616.29   189.3  617.14   198.8  617.88
   208.2  618.99   217.7  621.06   227.2  623.97
#Mann= 3 , 0 , 0
       0     .06       0   102.8    .045       0  126.66      .1       0
Bank Sta=102.8,126.66
XS Rating Curve= 0 ,0
Exp/Cntr=0.3,0.1

Type RM Length L Ch R = 1 ,9261.4  ,136.8,128.5,120.2
XS GIS Cut Line= 2
     1721401.151      486126.667     1721613.825      486046.806
#Sta/Elev= 28
       0   620.8     9.5  620.61    18.9   619.7    28.4  619.05    37.9  619.14
    47.3  618.73    56.8  616.46    66.3  613.48    75.7  611.62   81.71  610.84
    85.2   610.4    89.9  610.12    94.7  609.83   104.1  610.52   104.9  610.69
   113.6   612.5     123  614.52   132.5  614.83     142  614.24   151.4  614.31
   160.9  615.08   170.4  615.37   179.8  615.12   189.3  614.88   198.8  614.99
   208.2  615.23   217.7  615.72   227.2   616.3
#Mann= 3 , 0 , 0
       0     .09       0   81.71    .045       0   104.9     .08       0
Bank Sta=81.71,104.9
XS Rating Curve= 0 ,0
Exp/Cntr=0.3,0.1

Type RM Length L Ch R = 1 ,9132.9  ,408.3,407.2,402.8
XS GIS Cut Line= 3
     1721519.207      486227.361     1721612.957      486145.764
     1721711.047      486028.577
#Sta/Elev= 26
       0  616.15     9.6  617.05    19.1  616.37    28.7  613.55   33.22  611.89
    38.2  609.78    47.8   608.5    57.4  609.03    66.9  610.82    76.5  612.48
      86  612.91    95.6  612.77   105.2  612.78   114.7  613.31   124.3  613.96
   133.8  614.16     172  614.13   200.7  614.44   210.2  614.72   219.8  615.67
   229.4  619.22   238.9  624.48   248.4  630.14     258  634.94   267.6  638.06
   277.1  640.84
#Mann= 3 , 0 , 0
       0      .1       0   33.22    .045       0    47.8     .07       0
Bank Sta=33.22,47.8
XS Rating Curve= 0 ,0
Exp/Cntr=0.3,0.1

Type RM Length L Ch R = 1 ,8725.7  ,138.1,137.4,136.7
XS GIS Cut Line= 4
     1721769.207      486462.604     1721803.929      486381.875
     1721900.283      486257.743     1721948.026      486193.507
#Sta/Elev= 30
       0  622.62     9.8  620.37    19.5  617.75    29.3  616.98    39.1  616.88
    48.8  617.98    58.6  618.87    68.4  618.49    78.1   617.3    97.7  614.23
   107.5  613.16   127.2  612.39   156.6  611.47   166.4  611.26   176.3  610.07
   186.1  607.94   195.9  606.27   197.9  606.26   205.7  606.24   215.6  608.16
   225.4  611.01     245  615.66   253.9  618.82   262.8  624.63   271.7  632.28
   280.6  639.63   289.5  644.56   298.4  647.47   307.3  649.92     325   654.3
#Mann= 3 , 0 , 0
       0     .06       0   176.3    .045       0   197.9      .1       0
Bank Sta=176.3,197.9
XS Rating Curve= 0 ,0
Exp/Cntr=0.3,0.1

Type RM Length L Ch R = 1 ,8588.3  ,229.2,215.1,200.9
XS GIS Cut Line= 4
     1721896.811      486460.868     1721942.818      486426.146
     1722000.978      486346.285     1722026.151      486298.542
#Sta/Elev= 26
       0  616.22     9.6  617.19    19.2  617.58    28.8  617.27    38.4  616.62
      48  615.51    57.6  614.09    66.6  612.65    75.6   611.7    84.6  610.99
    93.6  610.43   102.6  610.02   111.5  608.72   120.1  607.02   120.5  606.94
   129.5     606   135.1  606.75   138.5  607.21   147.4  610.76   156.4   615.6
   165.4  621.82   174.4  629.77   183.4  637.46   192.4  643.83   201.4   648.1
   210.4   651.2
#Mann= 3 , 0 , 0
       0     .08       0   120.1    .045       0   138.5      .1       0
Bank Sta=120.1,138.5
XS Rating Curve= 0 ,0
Exp/Cntr=0.3,0.1

Type RM Length L Ch R = 1 ,8373.2  ,334.8,325.3,315.2
XS GIS Cut Line= 2
     1722158.964      486621.459       1722160.7      486341.945
#Sta/Elev= 28
       0  614.53    19.3  612.88    48.2  610.68    57.8   610.2    67.5  609.94
    77.1  610.22    86.8  611.15    96.4  612.21     106  612.76   115.7  612.12
   125.3     609   129.3  607.59   134.9  605.62   144.6  604.81   154.2  606.77
   163.9   608.8   173.5  609.01   183.1  609.46   192.8  610.89   202.4  614.92
     212  620.92   221.7  626.87   231.3  632.34     241  637.71   250.6  642.86
   260.2  646.87   269.9  649.78   279.5  652.34
#Mann= 3 , 0 , 0
       0      .1       0   129.3    .045       0   154.2      .1       0
#XS Ineff= 2 , 0
          106.55  618.83
Permanent Ineff=
       F       F
Bank Sta=129.3,154.2
XS Rating Curve= 0 ,0
Exp/Cntr=0.3,0.1

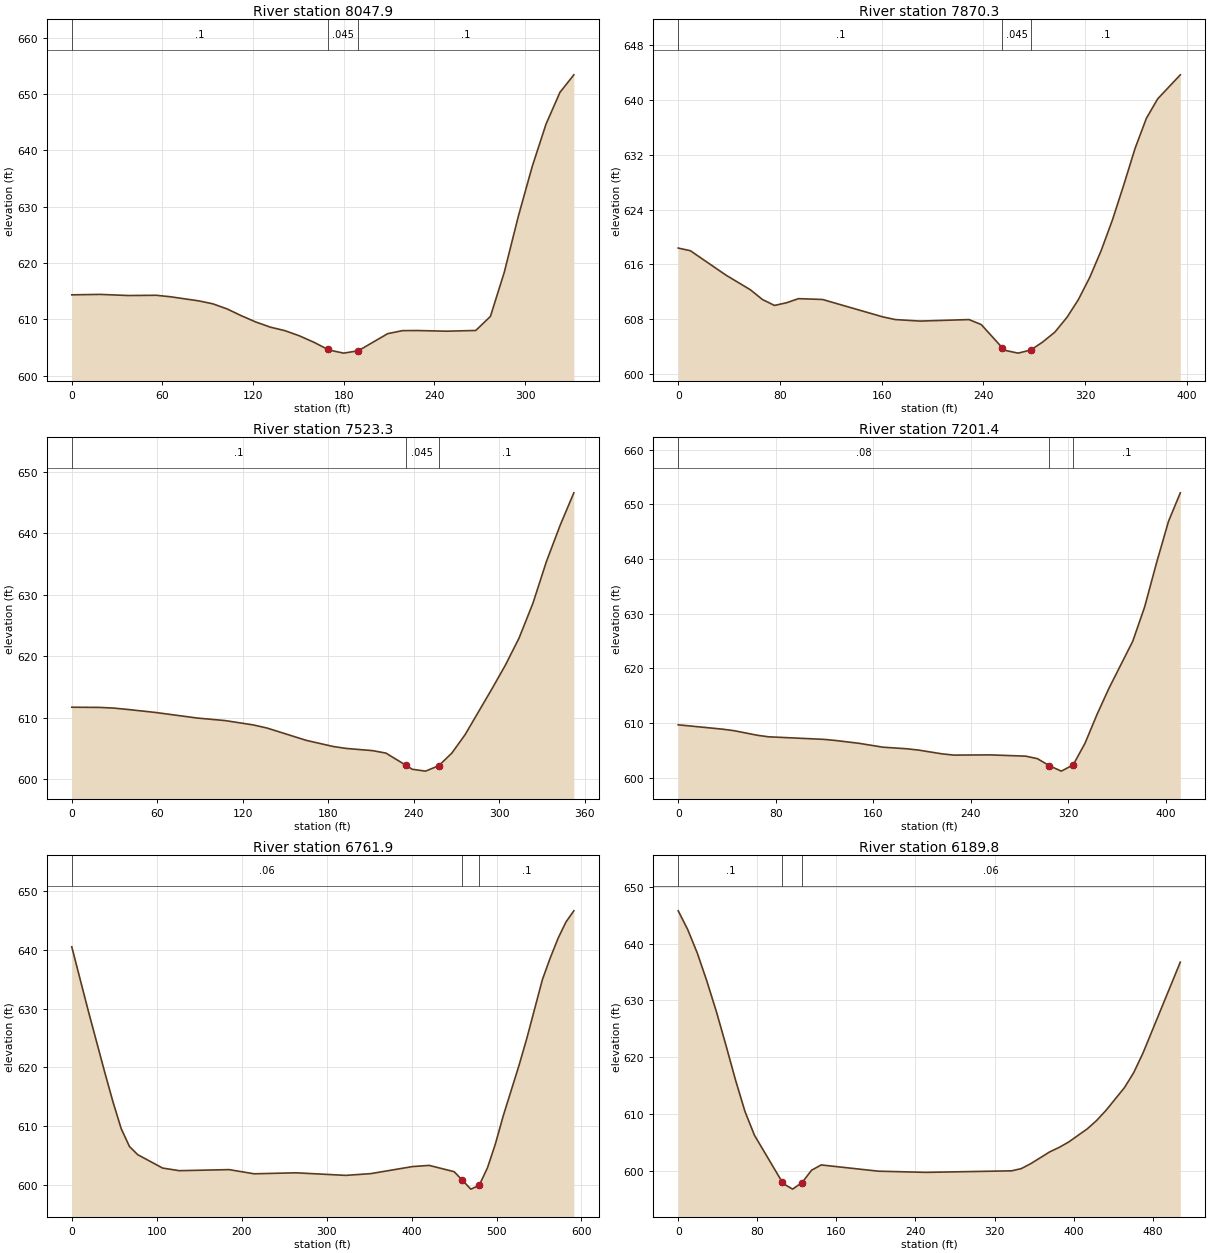
Type RM Length L Ch R = 1 ,8047.9  ,178.4,177.6,176.9
XS GIS Cut Line= 4
     1722475.804      486601.493     1722474.068      486489.514
     1722402.019      486341.077      1722383.79      486288.993
#Sta/Elev= 30
       0  614.37    18.7  614.45    37.3  614.25      56  614.29    65.3  614.03
      84   613.3    93.3  612.78   102.7  611.88     112  610.69   121.7  609.56
   131.4  608.64   141.1  608.01   150.8  607.08   160.5  605.92   169.4  604.69
   170.2  604.58   179.9  604.03   189.6  604.45     209  607.48   218.8  608.02
   228.5  608.04   247.9  607.92   267.3  608.05     277  610.54   286.2   618.4
   295.4  628.23   304.6  637.09   313.8  644.66     323  650.29   332.2   653.4
#Mann= 3 , 0 , 0
       0      .1       0   169.4    .045       0   189.6      .1       0
Bank Sta=169.4,189.6
XS Rating Curve= 0 ,0
Exp/Cntr=0.3,0.1

Type RM Length L Ch R = 1 ,7870.3  ,346.5,347,346.9
XS GIS Cut Line= 4
     1722648.547      486563.299     1722603.408       486428.75
     1722537.436      486278.577     1722521.811      486190.903
#Sta/Elev= 30
       0  618.39     9.5  618.01    37.8  614.42    56.8  612.31    66.2   610.9
    75.7  610.03    85.2  610.42    94.6  611.02   113.5   610.9   161.2  608.35
   170.9  607.97   190.2  607.75   228.8  607.97   238.4  607.24  255.09  603.83
   257.7  603.46   267.4  603.08   277.3  603.53   286.6  604.68   296.3  606.14
   305.9  608.31   314.8  610.88   323.8  614.14   332.7  618.01   341.6  622.49
   350.5  627.59   359.4  632.91   368.3   637.3   377.2  640.14     395  643.64
#Mann= 3 , 0 , 0
       0      .1       0  255.09    .045       0   277.3      .1       0
Bank Sta=255.09,277.3
XS Rating Curve= 0 ,0
Exp/Cntr=0.3,0.1

Type RM Length L Ch R = 1 ,7523.3  ,313,321.9,330.8
XS GIS Cut Line= 4
     1722918.512      486396.632     1722897.679      486261.216
     1722837.783      486115.382     1722806.533      486066.771
#Sta/Elev= 27
       0  611.75    19.6  611.72    29.4  611.61    39.2  611.39    58.7   610.9
    88.1  609.99   107.6  609.58   127.2  608.88     137  608.37   164.8  606.35
   183.4  605.37   192.6  605.05   211.2  604.69   220.5  604.29   234.5  602.32
     239  601.66   248.3  601.36   257.6  602.24   266.8   604.3   276.1   607.3
   294.7  614.65   304.3  618.57   313.9  622.97   323.6   628.6   333.2  635.47
   342.8  641.34   352.4  646.61
#Mann= 3 , 0 , 0
       0      .1       0   234.5    .045       0   257.6      .1       0
Bank Sta=234.5,257.6
XS Rating Curve= 0 ,0
Exp/Cntr=0.3,0.1

Type RM Length L Ch R = 1 ,7201.4  ,428.3,439.6,451.7
XS GIS Cut Line= 3
     1723109.484      486384.479     1723158.964      486255.139
       1723160.7      485981.702
#Sta/Elev= 27
       0   609.7    36.9  608.89    46.2  608.61    64.6   607.8    73.9  607.51
     120  607.03   129.2  606.83   148.2  606.32   167.8  605.61   187.3  605.32
   197.1  605.08   216.6  604.38   226.4  604.16   255.7   604.2     285  603.97
   294.7  603.51   304.5  602.21   314.3  601.23     324  602.37   333.8  606.36
   343.6  611.61   353.3  616.35   372.9  624.99   382.6  631.23   392.4  639.32
   402.2   646.9   411.9  652.12
#Mann= 3 , 0 , 0
       0     .08       0   304.5    .045       0     324      .1       0
Bank Sta=304.5,324
XS Rating Curve= 0 ,0
Exp/Cntr=0.3,0.1

Type RM Length L Ch R = 1 ,6761.9  ,570.9,572,570.5
XS GIS Cut Line= 4
     1723391.169       486507.96     1723407.445       486422.24
     1723600.587      486069.592     1723665.691      485991.467
#Sta/Elev= 30
       0  640.51    19.4  629.64    38.8  619.16    48.5  614.12    58.2  609.55
    67.9  606.52    77.6  605.13   106.9  602.85   126.5   602.4   185.3  602.58
   214.7  601.87   263.8  602.04   322.6   601.6     352   601.9   401.1   603.1
   420.7   603.3   450.1  602.23   459.9  600.76   469.7  599.26   479.5  599.88
   489.3  602.88   498.6  606.93   507.8   611.7   526.3  620.25   535.6   624.9
     554  634.94   563.3  638.65   572.5  641.98   581.8  644.76     591  646.64
#Mann= 3 , 0 , 0
       0     .06       0   459.9    .045       0   479.5      .1       0
Bank Sta=459.9,479.5
XS Rating Curve= 0 ,0
Exp/Cntr=0.3,0.1

Type RM Length L Ch R = 1 ,6189.8  ,192.7,198.6,204.5
XS GIS Cut Line= 3
     1723815.431      486640.339     1723999.892      486301.797
     1724013.998      486180.269
#Sta/Elev= 30
       0  645.76     9.6  642.46    19.3  638.32    28.9  633.42    38.6  628.01
    48.2  622.14    57.8  616.06    67.5  610.44    77.1  606.25   105.4  597.94
     106  597.76   115.7  596.76   125.3  597.92   134.9  600.09   144.6  601.02
   202.4  599.92   250.6  599.71   337.3  599.98     347  600.37   356.6  601.24
   375.9  603.33   385.5  604.12     395  605.06   413.8  607.37   423.2  608.84
   432.6   610.6   451.4  614.63   460.8  617.28   470.2  620.74   507.9  636.73
#Mann= 3 , 0 , 0
       0      .1       0   105.4    .045       0   125.3     .06       0
Bank Sta=105.4,125.3
XS Rating Curve= 0 ,0
Exp/Cntr=0.3,0.1