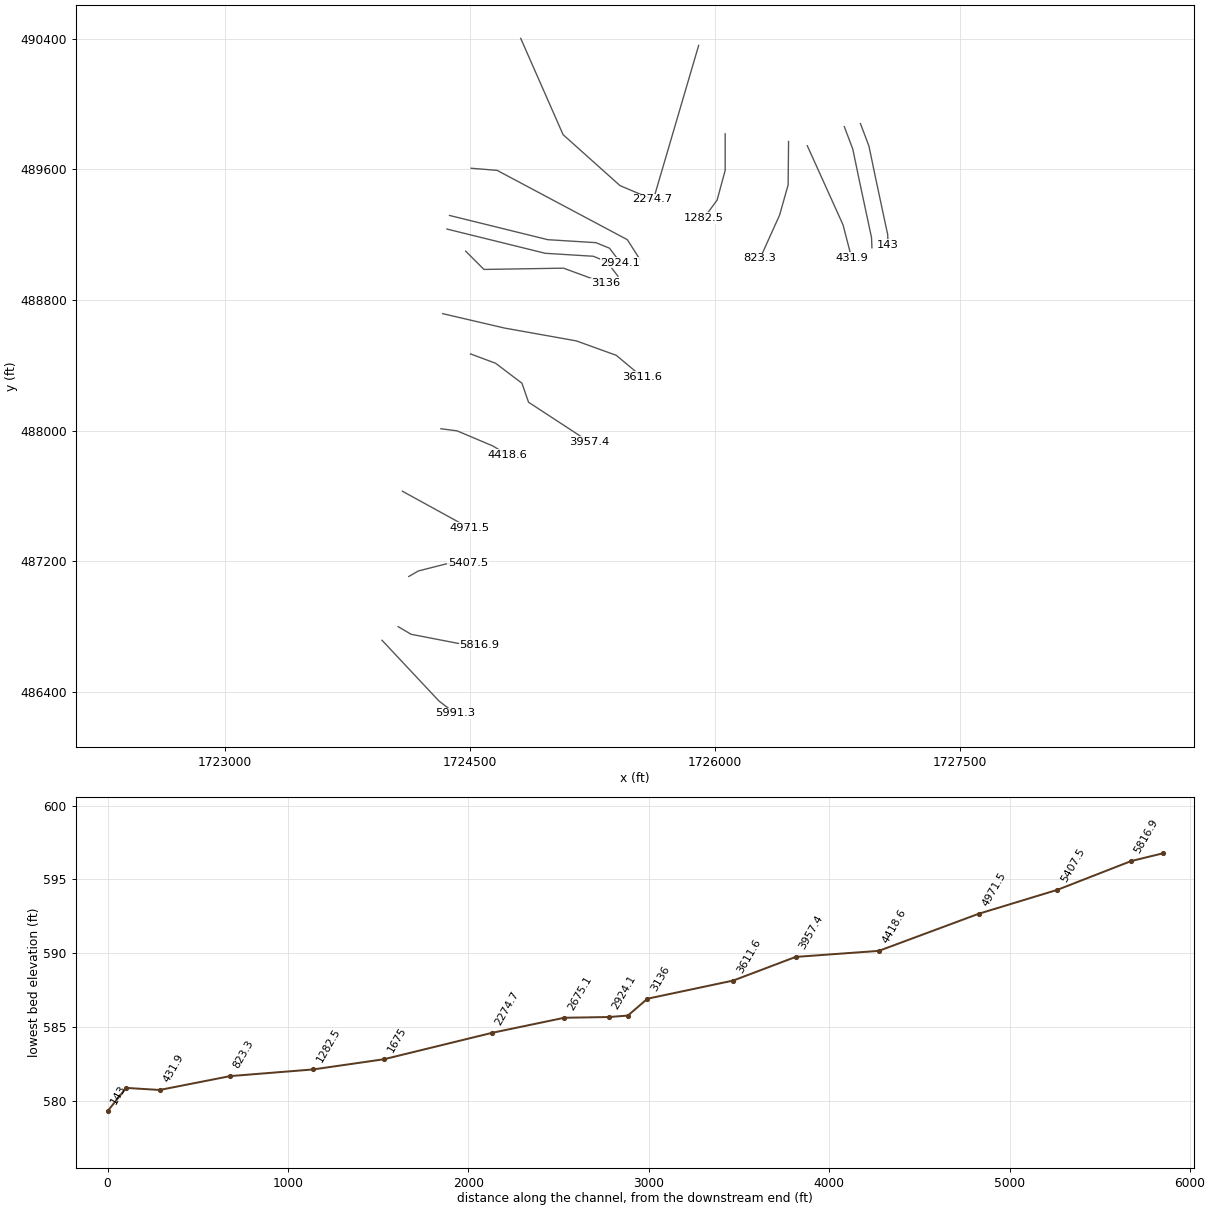
HEC-RAS study FALLSCK.prj: FALLSCK

--- FALLSCK.g01 (geometry) --- (continued)

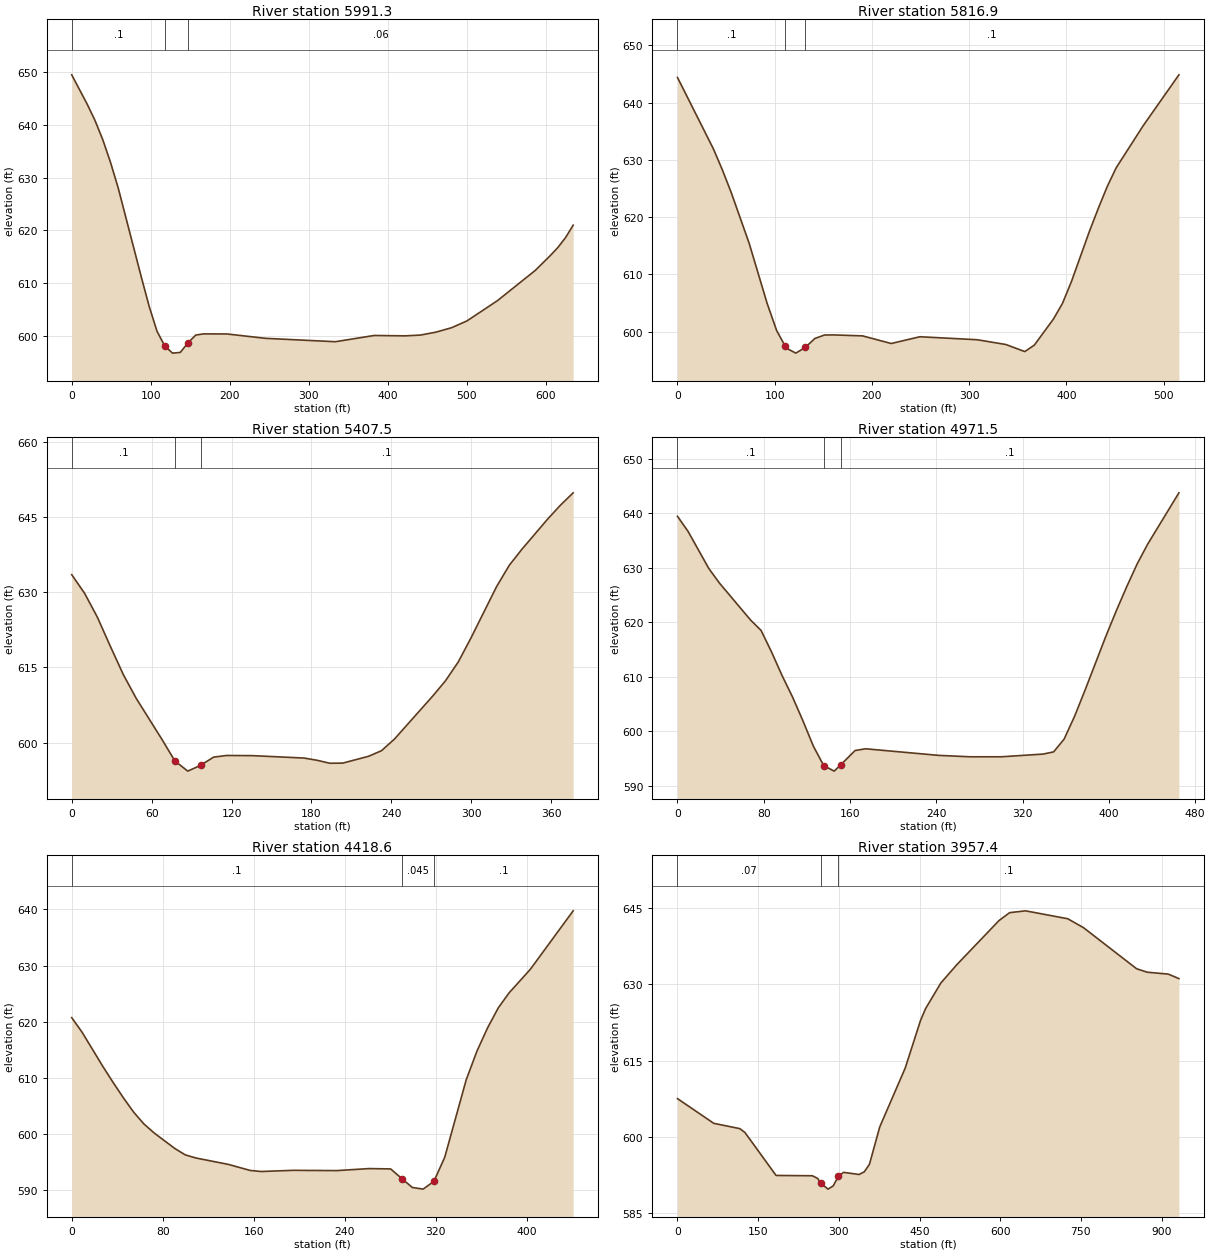
Type RM Length L Ch R = 1 ,5991.3  ,160,174.4,188.8
XS GIS Cut Line= 3
     1723960.613      486716.077     1724309.571      486343.681
      1724408.53       486268.16
#Sta/Elev= 30
       0  649.44    19.6  643.88    29.4  640.82    39.3  637.16    49.1  632.87
    58.9  627.99    88.3  611.04    98.1  605.58     108  600.89   117.8   598.1
   127.6  596.76   137.4  596.89   147.2  598.71     157  600.18   166.8   600.4
   196.3  600.39   245.4  599.56   333.7  598.92   382.8   600.1     422  600.03
   441.6  600.18   461.3  600.74   480.9  601.57   500.5  602.87   539.1  606.71
     587  612.44   606.1  615.26   615.7   616.8   625.2  618.64   634.8  620.98
#Mann= 3 , 0 , 0
       0      .1       0   117.8    .045       0   147.2     .06       0
Bank Sta=117.8,147.2
XS Rating Curve= 0 ,0
Exp/Cntr=0.3,0.1

Type RM Length L Ch R = 1 ,5816.9  ,398.6,409.4,419.1
XS GIS Cut Line= 4
     1724059.571       486799.41     1724138.998      486752.535
     1724428.061      486696.545     1724556.967      486690.035
#Sta/Elev= 30
       0  644.38    36.9  631.92    46.1  628.27    55.3  624.27    73.8  615.38
    92.2  604.93     102  600.18   110.9  597.42   111.9  597.11   121.7  596.24
   131.5  597.25   141.3   598.8   151.1   599.4   160.9  599.42   190.4  599.25
   219.8  597.92   249.3   599.1   308.2  598.58   337.6  597.75   357.2  596.51
     367  597.64   386.7   602.2   395.9  604.91   405.1  608.71   423.5  617.43
   432.8  621.52     442  625.34   451.2  628.61   478.9  635.94   515.7  644.84
#Mann= 3 , 0 , 0
       0      .1       0   110.9    .045       0   131.5      .1       0
Bank Sta=110.9,131.5
XS Rating Curve= 0 ,0
Exp/Cntr=0.3,0.1

Type RM Length L Ch R = 1 ,5407.5  ,453.6,436,419.3
XS GIS Cut Line= 4
     1724124.675      487106.702     1724183.269      487140.556
      1724352.54      487183.525     1724486.655      487187.431
#Sta/Elev= 30
       0  633.48     9.7  629.75    19.3  624.97      29  619.19    38.7  613.57
    48.3  608.86    67.7  600.64    77.4  596.34    87.1  594.29    96.8  595.45
   106.5  597.08   116.2  597.41   135.6  597.38   174.4   596.9   184.1  596.46
   193.8  595.86   203.5  595.89   222.9  597.25   232.6  598.37   242.3  600.68
   271.1  609.28   280.6   612.3   290.2  616.05   299.8  620.87     319   631.1
   328.6  635.38   338.2  638.61   357.3  644.56   366.9  647.33   376.5  649.81
#Mann= 3 , 0 , 0
       0      .1       0    77.4    .045       0    96.8      .1       0
Bank Sta=77.4,96.8
XS Rating Curve= 0 ,0
Exp/Cntr=0.3,0.1

Type RM Length L Ch R = 1 ,4971.5  ,551.3,553,554.3
XS GIS Cut Line= 2
     1724085.613      487628.837     1724493.165      487404.879
#Sta/Elev= 30
       0  639.43     9.7   636.7    29.1  629.84    38.8  627.21    67.8  620.39
    77.5   618.5    87.2  614.55    96.9  610.25   106.6  606.31   116.3  601.92
     126  597.26   135.6  593.68   145.3  592.67   151.5  593.85   164.7  596.45
   174.4  596.77   242.2  595.56   271.3   595.3   300.3   595.3   339.1   595.8
   348.8   596.2   358.5  598.53   368.2  602.71   377.8  607.45   397.2  617.39
   406.9  622.08   416.6  626.51   426.3   630.7     436  634.31     465  643.74
#Mann= 3 , 0 , 0
       0      .1       0   135.6    .045       0   151.5      .1       0
Bank Sta=135.6,151.5
XS Rating Curve= 0 ,0
Exp/Cntr=0.3,0.1

Type RM Length L Ch R = 1 ,4418.6  ,466.3,461.2,455.6
XS GIS Cut Line= 4
      1724321.29       488011.65     1724420.248      487998.629
     1724638.998      487906.181      1724727.54      487852.795
#Sta/Elev= 30
       0  620.71     9.1  618.12    27.2  612.07    36.3  609.19    45.4  606.43
    54.4  603.88    63.5  601.76    72.6  600.14    90.7  597.39    99.8  596.26
   109.3   595.7   137.8  594.56   156.8  593.49   166.3   593.3   194.8  593.51
   232.8  593.46   261.3  593.82   280.3  593.76   290.4  591.99   299.3  590.46
   308.8  590.16   318.3  591.54   327.8  595.82   346.7  609.64   356.1  614.73
   365.5   618.9   374.9  622.46   384.3  625.11   403.1  629.34   440.7  639.75
#Mann= 3 , 0 , 0
       0      .1       0   290.4    .045       0   318.3      .1       0
Bank Sta=290.4,318.3
XS Rating Curve= 0 ,0
Exp/Cntr=0.3,0.1

Type RM Length L Ch R = 1 ,3957.4  ,333.4,345.8,359.5
XS GIS Cut Line= 5
      1724502.28      488469.983     1724655.925      488412.691
     1724817.384      488290.295      1724857.55      488174.026
     1725227.974      487931.788
#Sta/Elev= 30
       0  607.55    67.5  602.69   115.8  601.65   125.4  600.89   183.3  592.44
   250.8  592.38   260.5  591.86   266.3  590.94   279.8  589.75   289.4  590.37
     299  592.24   308.7  593.05   337.6  592.63   347.3  593.15   356.9  594.64
     376  601.98   423.4  613.57   451.8  622.92   461.2  625.25   489.6  630.29
   519.1  633.87   597.8  642.58   617.5  644.13     647  644.49   725.6  642.93
   755.2  641.15   853.5   633.1   873.2  632.42   912.5  632.04   932.2  631.16
#Mann= 3 , 0 , 0
       0     .07       0   266.3    .045       0     299      .1       0
Bank Sta=266.3,299
XS Rating Curve= 0 ,0
Exp/Cntr=0.3,0.1

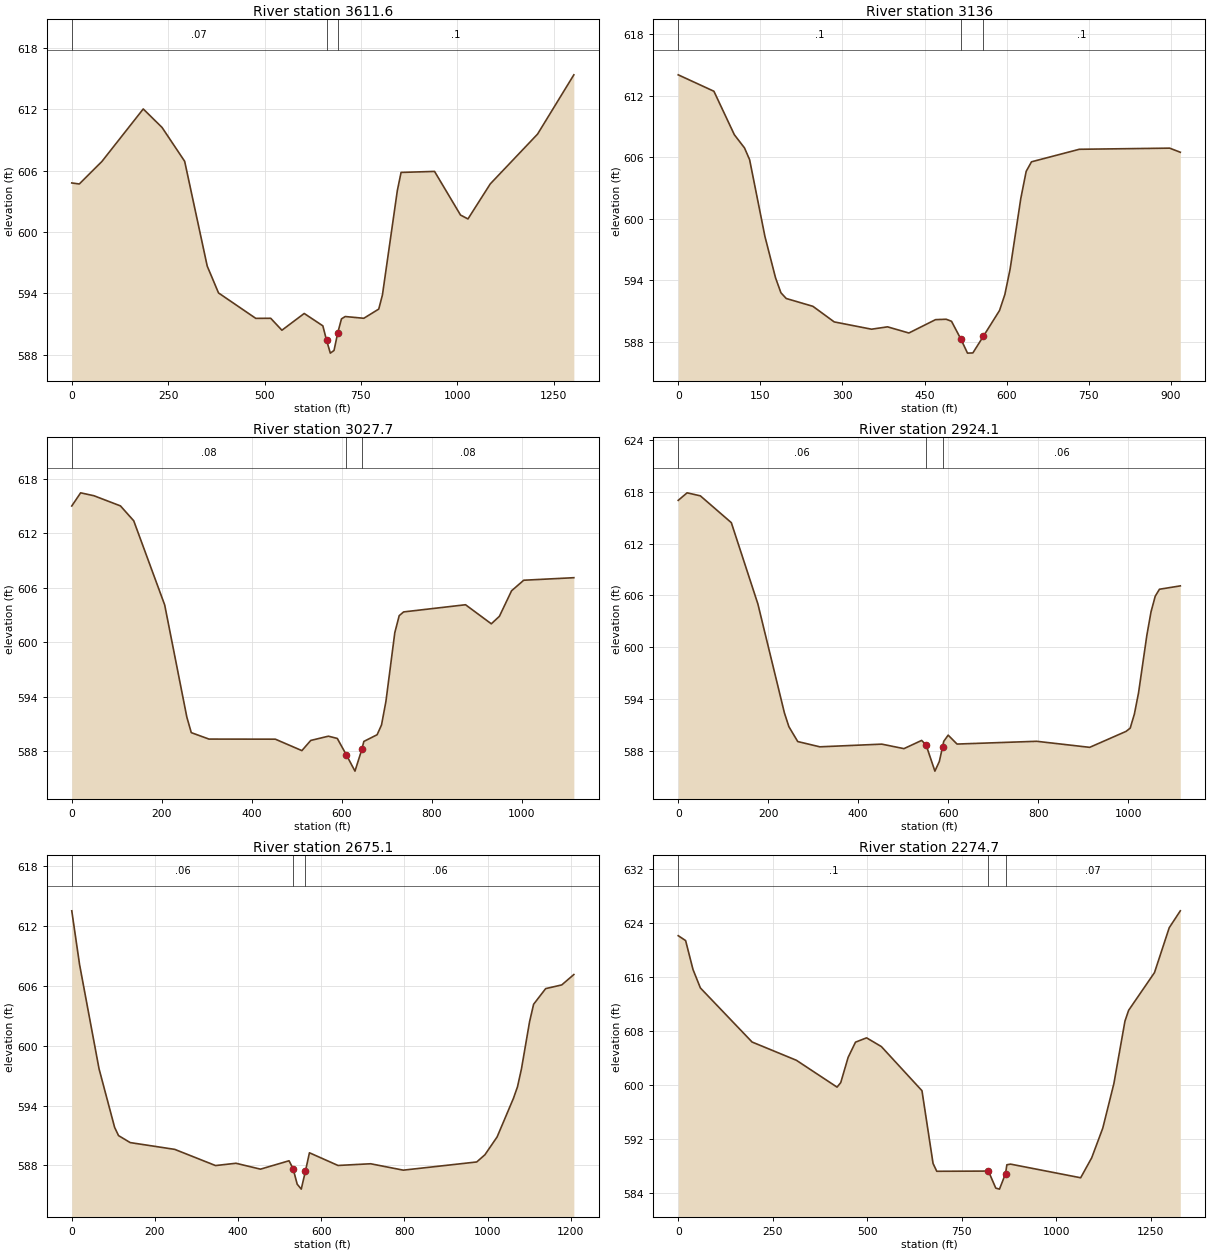
Type RM Length L Ch R = 1 ,3611.6  ,468.1,475.6,483.5
XS GIS Cut Line= 5
     1724332.141      488716.511     1724712.349      488627.969
     1725149.849      488549.844     1725394.641      488461.302
     1725553.495       488328.49
#Sta/Elev= 30
       0   604.8    19.5   604.7    78.1   606.9   185.4  612.04   234.2  610.23
   292.8  606.92   351.3  596.67   380.6  594.04   477.3  591.55     516  591.56
     545  590.39   602.9  592.03   651.2  590.82   660.9   589.4   670.6  588.15
   680.2  588.41   689.9  590.14   699.5   591.5   709.2  591.73   757.5  591.56
   796.2  592.46   805.8  593.85   844.4  604.05   854.1  605.83   940.9  605.93
  1008.3  601.66  1027.6  601.28  1085.5  604.71  1208.1  609.58  1302.2  615.38
#Mann= 3 , 0 , 0
       0     .07       0   660.9    .045       0   689.9      .1       0
Bank Sta=660.9,689.9
XS Rating Curve= 0 ,0
Exp/Cntr=0.3,0.1

Type RM Length L Ch R = 1 ,3136    ,114.5,108.3,101
XS GIS Cut Line= 4
     1724472.766      489099.323     1724584.745      488987.344
     1725071.724      488995.157     1725326.932      488901.407
#Sta/Elev= 30
       0  614.02    65.2  612.42   102.5  608.19   121.1   606.9   130.4  605.76
   158.4  598.28   177.8  594.25   187.6   592.8   197.3  592.24     246  591.48
     285  589.96   353.2  589.25   382.4  589.48   421.4  588.88   470.1  590.18
   489.6  590.22   499.3  590.02  516.39  588.29   528.5  586.92   538.3  586.94
   557.7  588.58     587  591.07   596.7  592.62   606.4  595.12   625.9  601.99
   635.7  604.62   645.4  605.55   732.8  606.77   897.9  606.88   917.3  606.48
#Mann= 3 , 0 , 0
       0      .1       0  516.39    .045       0   557.7      .1       0
Bank Sta=516.39,557.7
XS Rating Curve= 0 ,0
Exp/Cntr=0.3,0.1

Type RM Length L Ch R = 1 ,3027.7  ,104.2,103.6,100.8
XS GIS Cut Line= 5
     1724358.182       489234.74     1724959.745      489086.302
     1725254.016      489068.073     1725337.349      489034.219
     1725405.057      488945.677
#Sta/Elev= 30
       0  614.99    19.7  616.44    49.2  616.12   108.2     615   137.7  613.36
   206.5  604.09   255.7  591.74   265.6  590.02   304.9  589.31   452.4   589.3
   511.4  588.04   531.1  589.16   570.4  589.63   590.1  589.38   609.8  587.61
   629.4  585.78   644.7  588.18   649.1  589.05   678.6  589.79   688.4  590.87
   698.2  593.47   717.9  601.03   727.7  602.91   737.5  603.32   875.1  604.11
   932.4  602.01   950.4  602.84   977.4  605.65  1004.4  606.81  1115.8  607.09
#Mann= 3 , 0 , 0
       0     .08       0   609.8    .045       0   644.7     .08       0
Bank Sta=609.8,644.7
XS Rating Curve= 0 ,0
Exp/Cntr=0.3,0.1

Type RM Length L Ch R = 1 ,2924.1  ,254.7,249,243.4
XS GIS Cut Line= 5
     1724373.807      489318.073      1724975.37      489169.636
     1725269.641      489151.407     1725352.974      489117.552
     1725420.682      489029.011
#Sta/Elev= 30
       0  616.99    19.7  617.86    49.2  617.51     118  614.41     177  605.01
     236  592.41   245.9  590.82   265.6   589.1   314.7  588.49   452.4   588.8
   501.6  588.28   540.9  589.23   550.8  588.71   570.4  585.68   580.3   586.8
   587.3  588.46   590.1  589.13   599.9  589.84   619.6  588.81   796.5  589.13
   914.4  588.43   995.4  590.28  1004.4  590.65  1013.7  592.27    1023  594.74
  1041.5  601.41  1050.8  604.12  1060.1  605.91  1069.4  606.71  1115.8   607.1
#Mann= 3 , 0 , 0
       0     .06       0   550.8    .045       0   587.3     .06       0
Bank Sta=550.8,587.3
XS Rating Curve= 0 ,0
Exp/Cntr=0.3,0.1

Type RM Length L Ch R = 1 ,2675.1  ,404.7,400.4,396
XS GIS Cut Line= 4
      1724506.62      489607.136     1724665.474      489594.115
     1725462.349      489169.636     1725540.474       489047.24
#Sta/Elev= 30
       0   613.5    18.8  608.11    65.6  597.68   103.1  591.81   112.5  590.99
   140.6  590.29   247.7  589.61   345.8  587.99   394.9  588.22   453.8  587.63
   522.5  588.47   532.3  587.68   542.1  586.13   551.9  585.63   561.8   587.4
   571.6  589.27   640.3     588   718.8  588.17   797.3  587.53   973.9  588.35
   993.6  589.07    1023  590.86  1062.3  594.73    1072  595.88  1081.6  597.69
    1101  602.39  1110.7  604.14  1139.7  605.71  1178.4  606.08  1207.5  607.12
#Mann= 3 , 0 , 0
       0     .06       0   532.3    .045       0   561.8     .06       0
Bank Sta=532.3,561.8
XS Rating Curve= 0 ,0
Exp/Cntr=0.3,0.1

Type RM Length L Ch R = 1 ,2274.7  ,625.3,599.7,571.1
XS GIS Cut Line= 4
     1724809.571      490402.926      1725069.12      489812.865
     1725418.078      489500.365     1725615.995      489417.032
#Sta/Elev= 30
       0   622.1    19.5  621.38    39.1  617.09    58.6  614.37   195.3  606.37
   312.5  603.67     420   599.7   429.8  600.37   449.3   604.1   468.8  606.35
   498.1  606.99   537.2   605.7   644.6  599.17   673.9  588.41   683.7  587.25
   820.3  587.28   839.8  584.76   849.6  584.61  865.54  586.89   869.1  588.21
   878.8  588.31  1064.3  586.29  1093.5  589.25  1122.8  593.64  1152.1  600.22
  1181.4  609.46  1191.1  611.06  1259.5  616.64  1298.5  623.28  1327.8  625.78
#Mann= 3 , 0 , 0
       0      .1       0   820.3    .045       0  865.54     .07       0
Bank Sta=820.3,865.54
XS Rating Curve= 0 ,0
Exp/Cntr=0.3,0.1

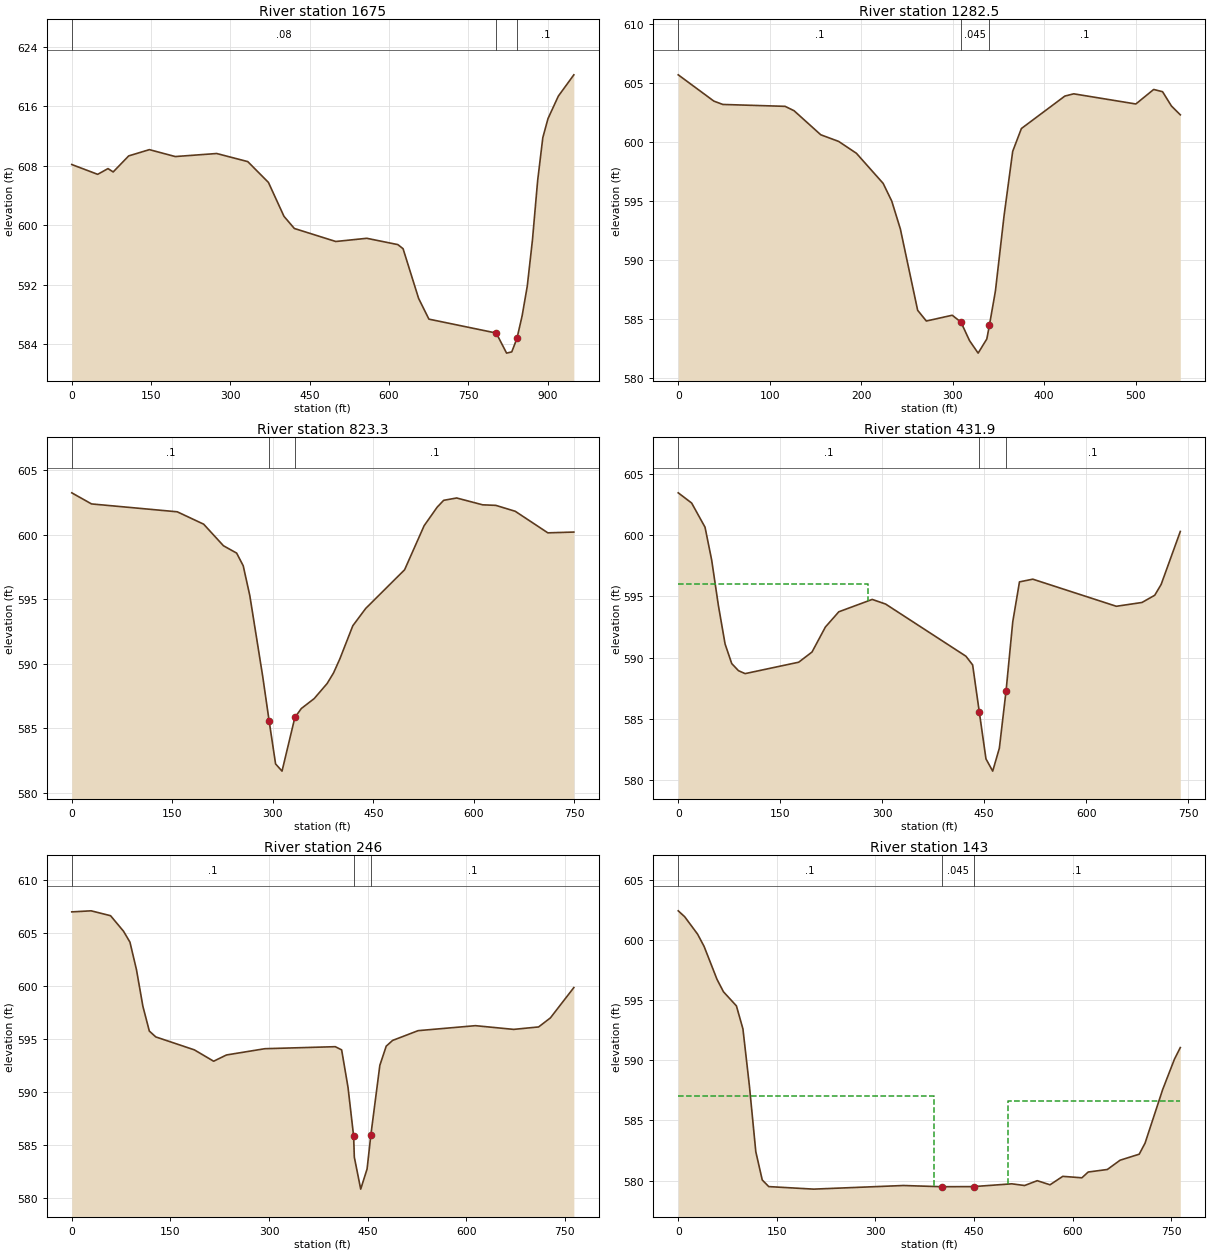
Type RM Length L Ch R = 1 ,1675    ,392.2,392.5,392.9
XS GIS Cut Line= 2
     1725898.981      490359.523      1725631.62      489448.282
#Sta/Elev= 30
       0  608.18      49  606.86    68.5  607.63    78.3  607.18   107.7  609.34
   146.8  610.18   195.8  609.25   274.1  609.66   332.9  608.57     372  605.77
   401.4  601.21     421  599.58   499.3  597.83     558  598.26   616.8  597.41
   626.6  596.86     656  590.18   675.5  587.39   802.8  585.52   822.4  582.82
   832.2  582.99     842   584.8   851.8  587.84   861.5  591.82   871.3  598.02
   881.1  605.99   890.9  611.79   900.7  614.35   920.3  617.38   949.6  620.24
#Mann= 3 , 0 , 0
       0     .08       0   802.8    .045       0     842      .1       0
Bank Sta=802.8,842
XS Rating Curve= 0 ,0
Exp/Cntr=0.3,0.1

Type RM Length L Ch R = 1 ,1282.5  ,459.6,459.2,458.7
XS GIS Cut Line= 4
     1726061.307      489818.073     1726061.307      489594.115
     1726011.828      489411.823     1725931.099      489302.448
#Sta/Elev= 30
       0  605.71      39  603.48    48.7   603.2   116.8  603.04   126.6  602.67
   155.8  600.63   175.3  600.07   194.8  599.06     224  596.51   233.4  595.01
   242.8  592.65   261.7  585.76   271.2  584.85   299.5  585.34     309  584.76
   318.4  583.19   327.8  582.13   337.3  583.33  340.12  584.48   346.7  587.39
   356.2   593.8   365.6  599.23   375.1  601.16   422.6  603.91   432.3   604.1
   500.2  603.24   519.7  604.47   529.4  604.28   539.1  603.07   548.8  602.32
#Mann= 3 , 0 , 0
       0      .1       0     309    .045       0  340.12      .1       0
Bank Sta=309,340.12
XS Rating Curve= 0 ,0
Exp/Cntr=0.3,0.1

Type RM Length L Ch R = 1 ,823.3   ,376,391.4,406.9
XS GIS Cut Line= 4
     1726449.328      489771.198     1726446.724      489505.573
     1726394.641      489320.677     1726274.849      489055.052
#Sta/Elev= 30
       0  603.24    29.5  602.38   157.4  601.77   196.8  600.81   226.3  599.14
     246  598.57   255.8  597.59   265.6  595.29   284.8  589.05   294.4  585.59
   304.1  582.24   313.7  581.68   332.9  585.84   342.5  586.53   361.7   587.3
   380.9  588.46   390.5  589.28   400.1  590.39   419.3  592.94   438.5  594.28
   496.6  597.28   525.7  600.69   545.2  602.13   554.9  602.66   574.3  602.84
   613.1  602.31   632.6  602.27   661.7  601.81   710.3  600.14   749.1   600.2
#Mann= 3 , 0 , 0
       0      .1       0   294.4    .045       0   332.9      .1       0
Bank Sta=294.4,332.9
XS Rating Curve= 0 ,0
Exp/Cntr=0.3,0.1

Type RM Length L Ch R = 1 ,431.9   ,191,185.9,180.6
XS GIS Cut Line= 3
     1726563.912      489745.157     1726782.662      489260.782
     1726834.745      489060.261
#Sta/Elev= 30
       0  603.43    19.7   602.6    39.4  600.63    49.2  597.95      59  594.27
    68.9  591.11    78.7  589.51    88.6  588.93    98.4  588.69   177.2  589.62
   196.8  590.45   216.5  592.49   236.2  593.73   285.4  594.74   305.1  594.36
   423.2  590.11   433.1   589.4   442.9  585.56   452.7  581.74   462.6  580.74
   472.4  582.61   482.3   587.3   492.1  592.91     502  596.17   521.6  596.39
   644.5  594.18   682.2  594.49     701  595.08   710.4  595.96   738.6  600.28
#Mann= 3 , 0 , 0
       0      .1       0   442.9    .045       0   482.3      .1       0
#XS Ineff= 2 , 0
          279.19  595.98
Permanent Ineff=
       F       F
Bank Sta=442.9,482.3
XS Rating Curve= 0 ,0
Exp/Cntr=0.3,0.1

Type RM Length L Ch R = 1 ,246     ,102.6,102.9,103.3
XS GIS Cut Line= 5
     1726790.474      489862.344     1726842.557      489724.323
     1726884.224      489523.802     1726957.141      489182.657
     1726959.745      489120.157
#Sta/Elev= 30
       0     607    29.5   607.1      59  606.64    78.7  605.18    88.5  604.15
    98.4  601.56   108.2   598.1     118  595.77   127.8  595.22   186.5     594
   215.8  592.93   235.3  593.52   293.8  594.11   400.8   594.3   410.5     594
   420.2  590.47   428.7  585.89   429.8  583.89   439.5  580.88   449.2  582.78
  454.92  585.97   468.6  592.54   478.3  594.35     488  594.89   526.8  595.81
     614  596.28   672.1  595.93   710.1  596.16     728  597.01   763.7  599.87
#Mann= 3 , 0 , 0
       0      .1       0   428.7    .045       0  454.92      .1       0
Bank Sta=428.7,454.92
XS Rating Curve= 0 ,0
Exp/Cntr=0.3,0.1

Type RM Length L Ch R = 1 ,143     ,145.7,143,140.3
XS GIS Cut Line= 5
     1726889.432      489880.573     1726941.516      489742.552
     1726983.182      489542.032     1727056.099      489200.886
     1727058.703      489138.386
#Sta/Elev= 30
       0   602.4     9.8  601.91    29.5  600.46    39.3  599.45      59  596.71
    68.8  595.68    88.5  594.51    98.4   592.6   108.2   587.9     118   582.4
   127.8  580.06   137.7  579.51     206   579.3   342.6   579.6   400.8   579.5
   449.2  579.51   507.4  579.74   526.8   579.6   546.1     580   565.5  579.66
   584.9  580.36     614  580.24   623.6  580.72   652.7  580.93   672.1   581.7
   701.2   582.2   710.1  583.12   736.9  587.57   754.8  590.09   763.7  591.05
#Mann= 3 , 0 , 0
       0      .1       0   400.8    .045       0   449.2      .1       0
#XS Ineff= 2 , 0
          388.31  587.05  500.97          586.63
Permanent Ineff=
       F       F
Bank Sta=400.8,449.2
XS Rating Curve= 0 ,0
Exp/Cntr=0.3,0.1

Chan Stop Cuts=-1
Use User Specified Reach Order=0
Composite Channel Slope=5